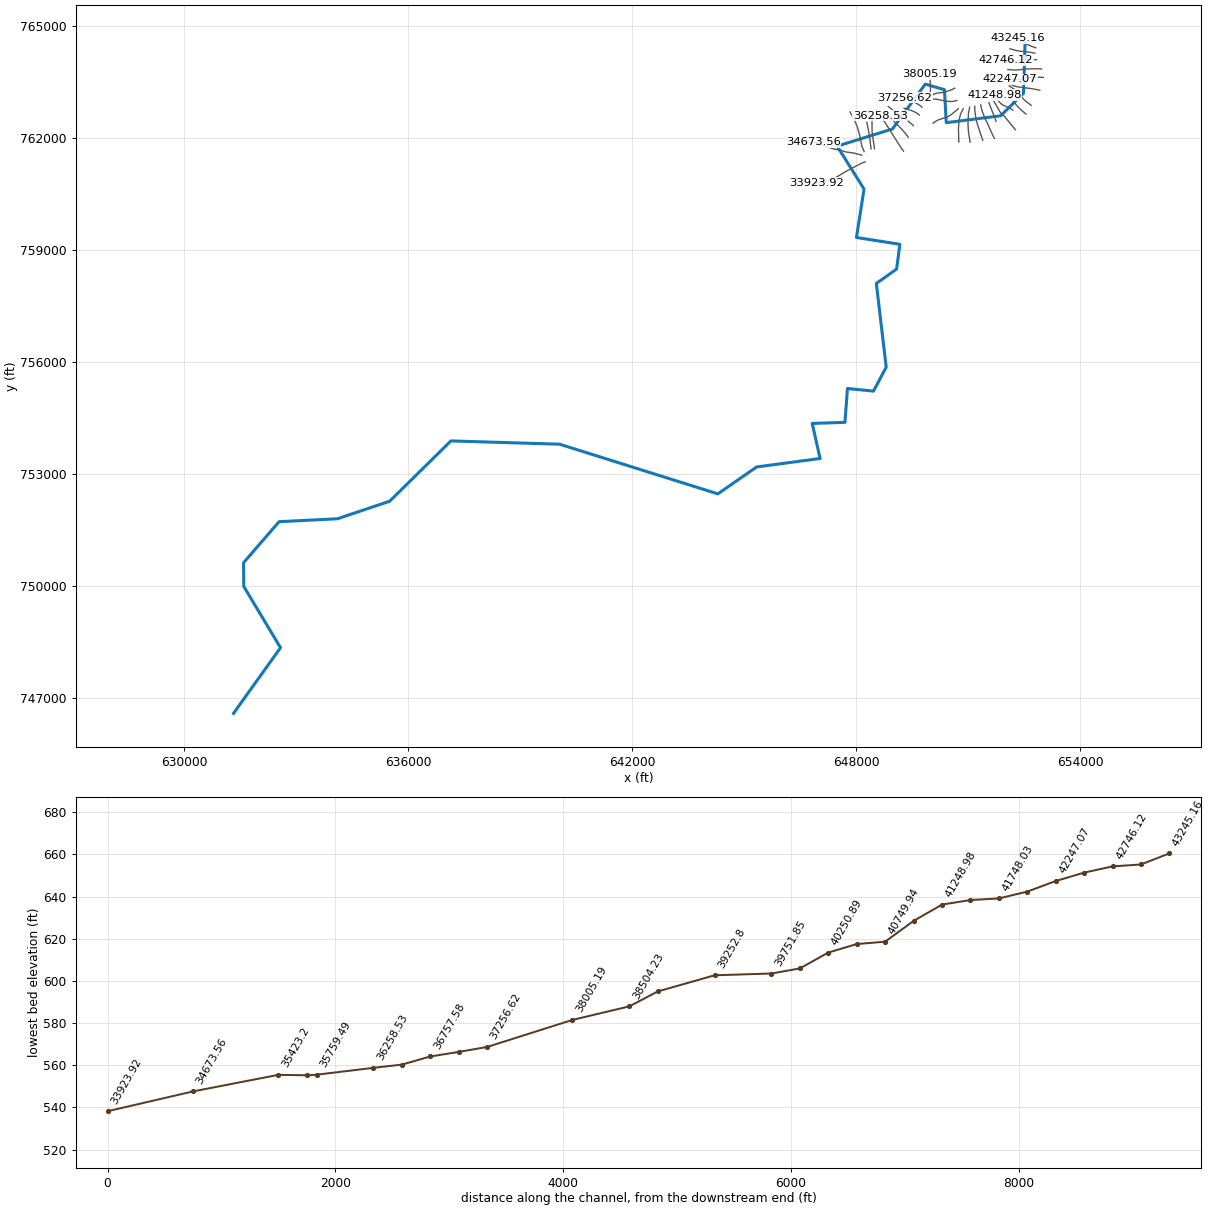
--- 3382_ras.prj (project) ---

Proj Title=3382
Current Plan=p01
Default Exp/Contr=0.3,0.1
English Units
Geom File=g01
Flow File=f01
Plan File=p01
Y Axis Title=Elevation
X Axis Title(PF)=Main Channel Distance
X Axis Title(XS)=Station
BEGIN DESCRIPTION:
RFD model 3382 exported to HEC-RAS
END DESCRIPTION:

--- 3382_ras.p01 (plan) ---

Plan Title=Plan 01
Program Version=4.10
Short Identifier=Plan 01
Geom File=g01
Flow File=f01
Subcritical Flow
Calc Critical at every XS
Secant Critical Depth

--- 3382_ras.f01 (steady flow) ---

Flow Title=Flow 01
Program Version=5.01
Number of Profiles= 6
Profile Names=10yr,25yr,50yr,100yr,100plus,500yr
River Rch & RM=3382,91,43245.16
 6279.9810541.8814730.8918698.5727299.9129600.66
River Rch & RM=3382,91,42995.64
 6281.2310544.0814734.0618702.7127305.9529606.67
River Rch & RM=3382,91,42746.12
 6283.7210548.4814740.4118710.9827318.0429618.69
River Rch & RM=3382,91, 42496.6
  6298.410574.3814777.7818759.7127389.1829689.44
River Rch & RM=3382,91,42247.07
 6316.5510606.2414823.6118819.3427476.2329775.46
River Rch & RM=3382,91,41997.55
 6318.0810608.9314827.49 18824.427483.6229782.79
River Rch & RM=3382,91,41748.03
 6320.16 10612.614832.79 18831.327493.6929792.78
River Rch & RM=3382,91,41498.51
 6329.7210629.4614857.0918862.9927539.9729838.74
River Rch & RM=3382,91,41248.98
 6333.7410636.5414867.3118876.3127559.4229858.05
River Rch & RM=3382,91,40999.46
 6530.9810975.7515349.1419496.0828464.2830725.17
River Rch & RM=3382,91,40749.94
  6532.510978.4215352.9919501.1128471.6230732.41
River Rch & RM=3382,91,40500.42
 6667.1711212.9815688.8319936.1529106.7931349.32
River Rch & RM=3382,91,40250.89
  6679.311234.5515720.0919977.0729166.5231408.73
River Rch & RM=3382,91,40001.37
 6681.4611238.3615725.6119984.2929177.0631419.17
River Rch & RM=3382,91,39751.85
  6684.7 11244.1 15733.919995.1329192.8831434.83
River Rch & RM=3382,91, 39252.8
 6696.9211265.8415765.4220036.4129253.1731494.82
River Rch & RM=3382,91,38753.76
 6709.22 11287.615796.88 20077.529313.1631554.12
River Rch & RM=3382,91,38504.23
 6711.5211291.6715802.7620085.1829324.3631565.19
River Rch & RM=3382,91,38005.19
 6724.8411315.1915836.7220129.5129389.0831628.99
River Rch & RM=3382,91,37256.62
 6732.6211329.0515856.8420155.8829427.5931667.38
River Rch & RM=3382,91, 37007.1
 6736.1611335.3715866.0220167.9329445.1831684.94
River Rch & RM=3382,91,36757.58
 7404.5512486.5517503.0122275.4332522.1334596.88
River Rch & RM=3382,91,36508.05
 7406.2212489.5417507.3522281.1232530.4334605.04
River Rch & RM=3382,91,36258.53
 7408.2612493.1917512.6622288.0932540.6234615.09
River Rch & RM=3382,91,35759.49
 7435.77 12542.417584.2822382.19   3267834750.66
River Rch & RM=3382,91,35673.08
 7574.81 12788.317939.7622846.5333355.9335409.25
River Rch & RM=3382,91, 35423.2
 7576.4612791.2517944.0522852.1733364.1635417.35
River Rch & RM=3382,91,34673.56
 7627.9412882.3318075.7623024.2433615.3935661.04
River Rch & RM=3382,91,33923.92
 7666.7112950.7518174.5223153.1133803.5435842.75
River Rch & RM=3382,91,33674.04
 7667.8412952.7718177.4723156.99 33809.235848.33
River Rch & RM=3382,91,33424.17
 7669.3312955.4518181.3923162.1533816.7335855.77
River Rch & RM=3382,91,33174.29
 7682.0912978.3518214.7723206.0733880.8635918.93
River Rch & RM=3382,91,32924.41
  7683.712981.2418218.9923211.64   3388935926.98
River Rch & RM=3382,91,32674.53
 7686.0412985.4618225.1723219.7833900.8835938.74
River Rch & RM=3382,91,32424.65
 7686.6612986.5718226.7923221.9333904.0135941.84
River Rch & RM=3382,91,31924.89
 7820.4413222.2718566.7623665.1334551.0936564.21
River Rch & RM=3382,91,31175.25
 7843.4413263.5418626.9523744.3634666.7736677.87
River Rch & RM=3382,91,30925.37
 7846.7713269.5418635.71 23755.934683.6136694.45
River Rch & RM=3382,91,30175.73
 8004.0613547.7519037.9924281.4835450.9637433.73
River Rch & RM=3382,91,29426.09
 8141.5413793.9819396.7124753.22 36139.738105.66
River Rch & RM=3382,91,29176.21
 8144.8313799.9119405.3724764.6436156.3838121.99
River Rch & RM=3382,91,28926.33
 8342.9314158.0719930.1725458.1837168.9539117.79
River Rch & RM=3382,91,28676.45
 8343.8814159.7919932.6925461.5237173.8139122.58
River Rch & RM=3382,91,28426.57
 8344.6914161.2819934.8725464.4137178.0439126.77
River Rch & RM=3382,91,28176.69
 8352.1514174.8619954.8625490.9237216.7539165.07
River Rch & RM=3382,91,27926.82
 8352.7514175.9319956.4425493.0137219.7939168.06
River Rch & RM=3382,91,27676.94
 8354.5114179.1319961.1425499.2437228.8939177.04
River Rch & RM=3382,91,27427.06
 8355.6814181.2719964.2725503.3937234.9539183.02
River Rch & RM=3382,91,27177.18
 8356.6314182.9919966.7925506.7337239.8239187.81
River Rch & RM=3382,91, 26927.3
 8358.2514185.9419971.1525512.5137248.2639196.18
River Rch & RM=3382,91,26677.42
 8361.3414191.59 19979.525523.6137264.4739212.33
River Rch & RM=3382,91,26427.54
 8364.1614196.7919987.1825533.8537279.4339227.28
River Rch & RM=3382,91,25927.78
 8367.1914202.3719995.4525544.8837295.5339243.43
River Rch & RM=3382,91,25428.02
 8368.6514205.0519999.4325550.1937303.28 39251.2
River Rch & RM=3382,91, 24428.5
 8397.4114257.8320077.41   2565437454.8439402.35
River Rch & RM=3382,91,23495.11
 8459.5514371.3320244.7425876.2937779.39 39724.2
River Rch & RM=3382,91,22015.05
 8482.1814413.1220306.7525959.1337900.3339845.52
River Rch & RM=3382,91,21049.67
 9535.1816221.8822875.4229261.1942721.3344216.91
River Rch & RM=3382,91,20566.98
 9554.4616257.2822927.7929330.9542823.1944316.71
River Rch & RM=3382,91,20084.29
 9564.8116276.1722955.62 29367.942877.1344369.15
River Rch & RM=3382,91,19118.91
 9593.1316328.3523032.9529471.0843027.7744517.19
River Rch & RM=3382,91,18153.53
10025.6217069.5424084.0830820.4544997.8546274.48
River Rch & RM=3382,91,17670.84
10033.3317083.7124105.0730848.4245038.6946314.27
River Rch & RM=3382,91,17188.15
10066.3517142.9724191.5330962.2745204.9246471.59
River Rch & RM=3382,91,16705.46
10083.9617175.5824240.0131027.1145299.5746564.43
River Rch & RM=3382,91,16222.77
10151.2117294.8624412.85 31253.345629.8246872.08
River Rch & RM=3382,91,15740.08
10200.8217386.7324549.4131435.9745896.5247133.32
River Rch & RM=3382,91, 15257.4
10228.63 17438.424626.3731539.0946047.0747281.23
River Rch & RM=3382,91,14774.71
10236.0917452.6724647.9831568.4346089.9147324.57
River Rch & RM=3382,91,14292.02
10292.8717560.2924810.0631787.6346409.9447645.24
River Rch & RM=3382,91,13809.33
10296.4717567.3824820.9831802.6346431.8447667.95
River Rch & RM=3382,91,13326.64
10329.3917631.85 24919.831938.1946629.7547872.19
River Rch & RM=3382,91,12843.95
10333.0317639.1224931.0531953.7346652.4547895.96
River Rch & RM=3382,91,12361.26
 10340.517654.0624954.2131985.7946699.2647945.17
River Rch & RM=3382,91,11878.57
10342.8317658.7524961.4931995.8746713.9747960.64
River Rch & RM=3382,91,11172.76
10344.4817662.0724966.6532003.0446724.4347971.69
River Rch & RM=3382,91,10939.26
10345.6217664.31 24970.132007.7846731.3647978.87
River Rch & RM=3382,91,10773.38
10346.7817666.5924973.5932012.5646738.3447986.06
River Rch & RM=3382,91,10629.37
10464.4617882.46 25292.832437.7147359.0748585.71
River Rch & RM=3382,91,10437.73
10497.2217949.0625396.8832582.6647570.6948810.38
River Rch & RM=3382,91,9803.525
 10498.117950.8425399.6732586.5647576.3848816.42
River Rch & RM=3382,91,9598.577
10527.6118012.5625497.4632724.1947777.32 49034.1
River Rch & RM=3382,91,9332.884
10528.9818015.3325501.7832730.21 47786.149043.41
River Rch & RM=3382,91,8609.987
10614.3218179.8525751.9933071.3248284.1349548.55
River Rch & RM=3382,91,7887.089
10621.6718195.2725776.4533105.7948334.45 49603.1
River Rch & RM=3382,91,6042.141
10742.9618447.3226174.8533665.6349151.8250483.52
Boundary for River Rch & Prof#=3382,91,1
Up Type= 0
Dn Type= 2
Boundary for River Rch & Prof#=3382,91,2
Up Type= 0
Dn Type= 2
Boundary for River Rch & Prof#=3382,91,2
Up Type= 0
Dn Type= 2
Boundary for River Rch & Prof#=3382,91,2
Up Type= 0
Dn Type= 2
Boundary for River Rch & Prof#=3382,91,2
Up Type= 0
Dn Type= 2
Boundary for River Rch & Prof#=3382,91,2
Up Type= 0
Dn Type= 2

--- 3382_ras.g01 (geometry) ---

Geom Title=3382
Program Version=4.10

River Reach=3382,91
Reach XY= 30
652517.971674681764549.092002615652475.989364743763195.948326528
651863.339992255762592.620120078650406.155152351762407.673335612
650357.722154796763292.234807163649843.764549375763440.518477932
648965.969471335762240.068002686647485.079138756761778.574618101
648204.402140349760629.536083907648000.916413069 759332.87346369
649162.674188465759150.360920921649077.716912657758488.537214071
648533.353937656758101.212986395 648797.23369056755859.734397277
648458.316155851755218.089869455647759.907301605755287.685786158
647692.606952131754381.384811446646816.330912948754352.789952829
647026.400357336753413.553841725 645328.19380486753186.390232682
644288.119107485752465.637175053640049.837857306753795.932313919
637138.227247924753883.967581272635497.630647957  752268.1637806
634099.672936022751798.489333823632536.052233249751720.381700724
631585.231292278750621.375605464  631590.4396258749985.958938807
632574.814625621748345.333938792631315.821269274746586.278210744

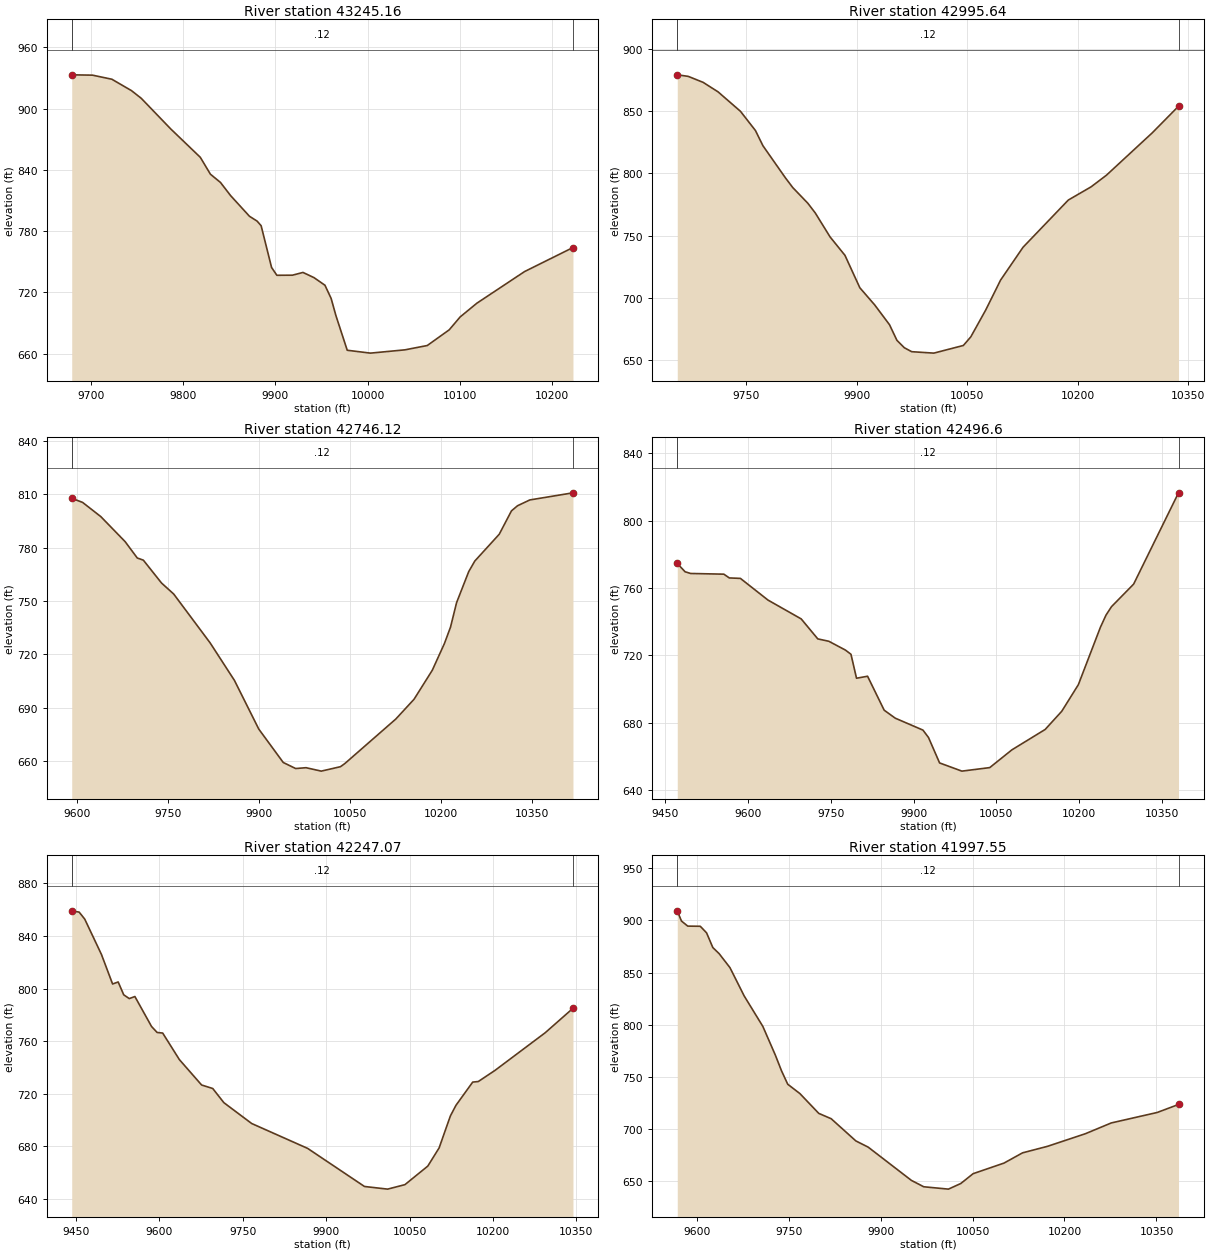
Type RM Length L Ch R = 1 ,43245.16,249.522600,249.522600,249.522600
XS GIS Cut Line= 6
652806.497778055764413.708898685652680.266750351764457.551503825
652626.172830279764481.155760854652577.194074822764506.997131414
652477.247860963764578.214032606652329.320750328764666.761844307
#Sta/Elev= 30
9679.165933.10159701.699932.77599722.663 928.7869743.899917.64629754.547910.0846
 9786.49880.09729818.572852.27459829.483835.77789840.393827.70089851.304814.8819
9871.845794.53989880.084789.83279884.478785.28669895.784744.42159901.513736.7578
9918.397 736.8399929.836739.54079941.746 734.4669953.656727.00889960.369714.0145
9965.566697.18689977.809663.323410002.95660.506410040.35663.724410064.57667.9629
10088.34683.317210100.23695.974210118.31709.397910170.05740.402810222.48763.9111
#Mann= 3 , 0 , 0
9679.165    0.12       09679.165    0.12       010222.48    0.12       0
#XS Ineff= 2 , 0
       0                               0
Bank Sta=9679.165,10222.48
Exp/Cntr=0.3,0.1

Type RM Length L Ch R = 1 ,42995.64,249.522600,249.522600,249.522600
XS GIS Cut Line= 6
652779.506524768764269.755547825652593.714467964764302.044793868
652373.772858485 764323.87598022652325.156064769764331.805897601
652259.100164199764345.895786972652111.079262318764387.640477607
#Sta/Elev= 30
9656.541879.47939671.289878.26349691.621873.42179711.927865.75719742.363850.0708
9762.654834.60539772.799822.37469803.235796.5709 9813.38788.59989833.671776.0848
9843.816768.22389863.995748.85349884.167 734.0369904.338707.94159924.509694.1062
9944.613678.17119954.636665.62689964.659659.64279974.682656.422910004.75655.2633
10044.89661.441410054.95668.371810075.13689.909210095.39714.115110125.88740.5671
10187.29 778.57810218.34789.276710239.05   798.610301.27832.744310336.87854.1649
#Mann= 3 , 0 , 0
9656.541    0.12       09656.541    0.12       010336.87    0.12       0
#XS Ineff= 2 , 0
       0                               0
Bank Sta=9656.541,10336.87
Exp/Cntr=0.3,0.1

Type RM Length L Ch R = 1 ,42746.12,249.522600,249.522600,249.522600
XS GIS Cut Line= 6
652822.839989399764093.995466016652555.141060896764102.634390744
652487.423772098 764096.93031663652353.986971367764058.860718926
652250.388135072764051.143580467652005.234170808 764079.47322134
#Sta/Elev= 30
9591.326807.66219609.242805.34849639.301797.35619679.346783.30559699.369774.1076
 9709.38 772.8969739.414760.01869759.432 753.8539819.432726.41499859.433705.3653
9899.575677.99129939.974659.1859 9960.46655.79069977.494656.265610002.62654.3364
10034.27656.8233 10041.5 658.60110125.56683.633110155.59694.742610185.62 711.031
10205.64726.062210215.64735.239210225.65749.016310245.67 766.46310255.71772.4086
10295.96787.452810316.09800.582410326.15803.480110346.42806.736410417.47810.7321
#Mann= 3 , 0 , 0
9591.326    0.12       09591.326    0.12       010417.47    0.12       0
#XS Ineff= 2 , 0
       0                               0
Bank Sta=9591.326,10417.47
Exp/Cntr=0.3,0.1

Type RM Length L Ch R = 1 , 42496.6,249.522600,249.522600,249.522600
XS GIS Cut Line= 6
652959.137251572763847.362324963652717.459442879763851.786364362
652571.275549597763845.324701223652304.999464299 763819.91519148
652206.884786613763818.847149806652054.396916103763831.521984137
#Sta/Elev= 30
9472.461774.59789486.627769.66659496.635768.65799556.679768.24629566.686766.0077
9586.701765.74289636.708752.85459696.709741.70249726.721729.84919746.741  728.43
 9776.77723.1962 9786.78720.7147 9796.79706.51049816.809707.68869846.838687.5538
9866.871 682.8089917.025675.73359927.056671.34399947.117656.25659987.454651.3908
10037.88653.482410078.06664.037610138.17 676.11610168.17686.903510198.18702.6631
10238.19736.7992 10248.2743.929810258.21748.979710298.26762.360710379.41816.5054
#Mann= 3 , 0 , 0
9472.461    0.12       09472.461    0.12       010379.41    0.12       0
#XS Ineff= 2 , 0
       0                               0
Bank Sta=9472.461,10379.41
Exp/Cntr=0.3,0.1

Type RM Length L Ch R = 1 ,42247.07,249.522600,249.522600,249.522600
XS GIS Cut Line= 6
653008.316951249 763618.84896214652884.365358566763627.523004423
652657.263575235 763622.80603112652341.913511256763557.320987009
652210.033996585763551.630976981652115.717573766 763564.33193354
#Sta/Elev= 30
9442.424859.11319455.794858.12549465.817852.82759495.887825.92329515.933803.4424
9525.956 805.0039535.979795.21339546.003792.34529556.026 793.9249586.051771.0972
9596.052766.57229606.052766.12399636.054745.94859676.056726.61659696.069723.9529
9716.101713.17569766.179697.30129866.823678.37899969.024649.410410010.65647.3995
10041.81650.811210082.91664.919510103.27 678.74310123.54703.070310133.58711.1658
 10163.7728.826210173.75729.2513 10203.8737.726410294.02766.334710344.03784.9447
#Mann= 3 , 0 , 0
9442.424    0.12       09442.424    0.12       010344.03    0.12       0
#XS Ineff= 2 , 0
       0                               0
Bank Sta=9442.424,10344.03
Exp/Cntr=0.3,0.1

Type RM Length L Ch R = 1 ,41997.55,249.522500,249.522500,249.522500
XS GIS Cut Line= 6
652911.659604565763276.662397134652764.729206631763307.163177063
652671.315381546763322.006245164652316.974361931763366.738330215
652217.471968099763394.455257857652113.310141559763436.397829473
#Sta/Elev= 30
9568.383909.12879575.208899.36189585.455894.4779 9605.95894.31869616.197888.0276
9626.445873.88419636.692 868.0889654.361 854.6349677.446827.63389708.001798.3114
9728.313770.91129738.439755.77589748.564742.92159768.401733.96999799.192714.9849
9819.405709.88149859.672688.59449879.806682.63159950.273650.76089970.406644.6489
10010.69642.387610030.84647.775310050.99657.204210101.36667.351810131.62677.1732
10172.31683.416910234.27695.530510276.25705.811310351.36715.881310385.95723.5212
#Mann= 3 , 0 , 0
9568.383    0.12       09568.383    0.12       010385.95    0.12       0
#XS Ineff= 2 , 0
       0                               0
Bank Sta=9568.383,10385.95
Exp/Cntr=0.3,0.1

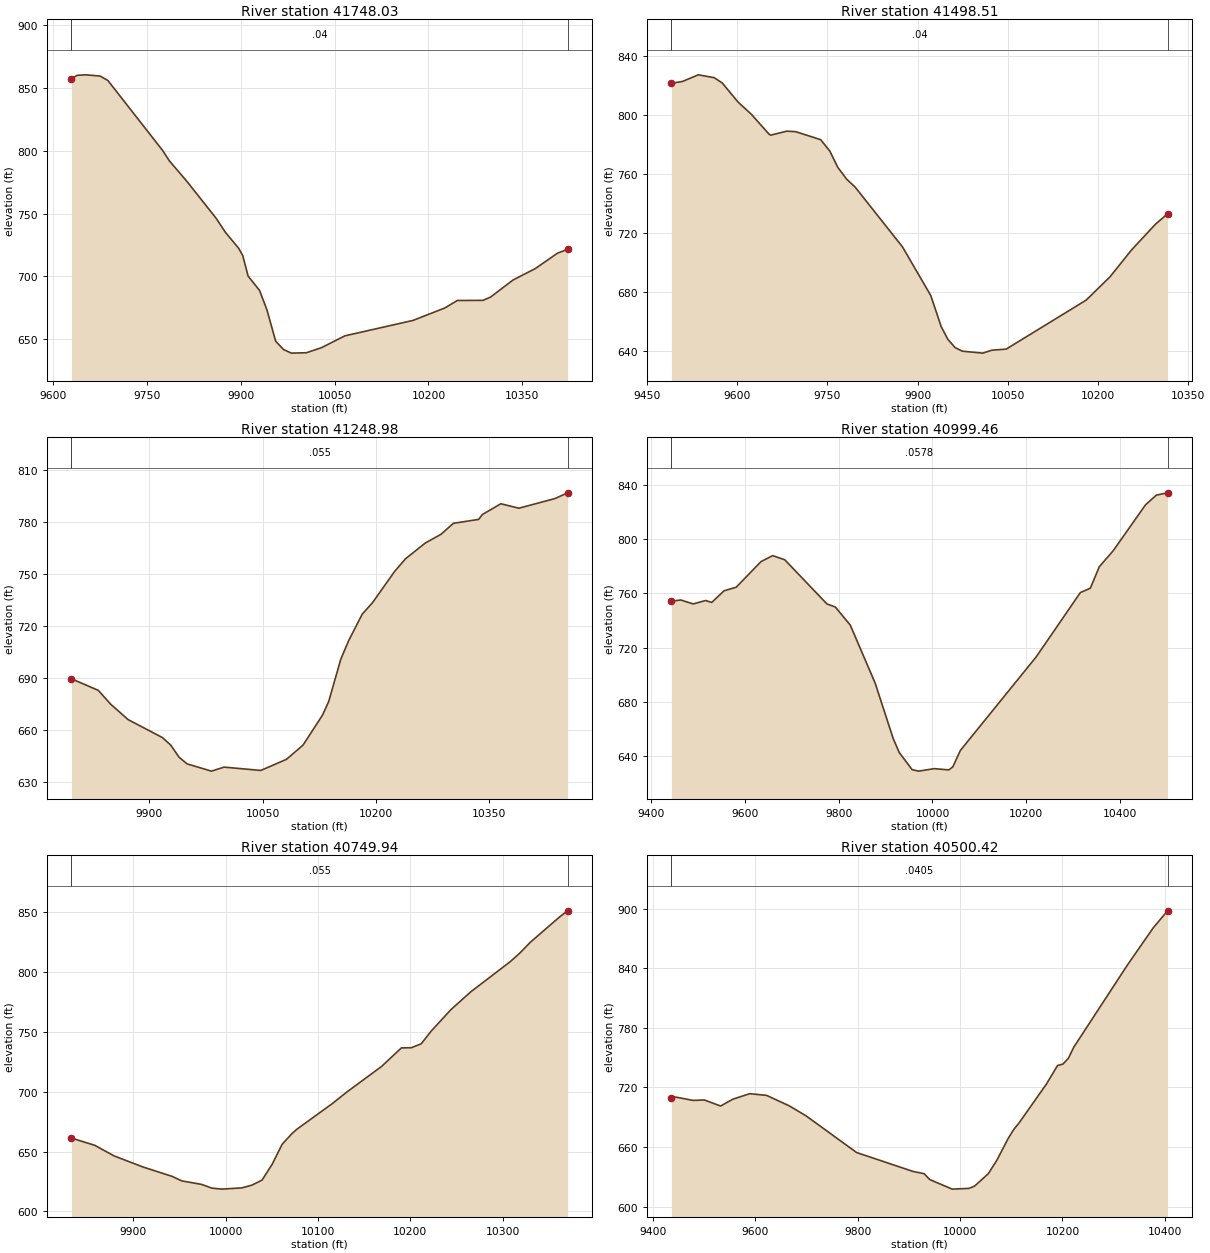
Type RM Length L Ch R = 1 ,41748.03,249.522600,249.522600,249.522600
XS GIS Cut Line= 6
652682.555115538762872.128567178652555.451167938762965.985611846
652476.748715122763038.128428402652330.588552302763220.640843374
 652236.88238031 763296.52766717 652091.30590735763391.472517956
#Sta/Elev= 30
9628.957 857.0899638.019859.74769651.739 860.1429674.826859.15439687.131855.6812
9774.878800.02029785.413791.92199814.148775.21779860.828745.93719875.093735.1478
9896.454722.37349903.012716.58849911.511700.33539929.764689.00399941.625673.5062
9955.641648.59769968.188641.99999980.716639.147810004.73639.443110028.84643.4476
10066.28652.863510175.25665.104710226.07674.967610246.27680.962510287.36681.0562
10299.46683.686310335.21697.168110371.04706.326210406.46718.523510422.63 721.565
#Mann= 3 , 0 , 0
9628.957    0.04       09628.957    0.04       010422.63    0.04       0
#XS Ineff= 2 , 0
       0                               0
Bank Sta=9628.957,10422.63
Exp/Cntr=0.3,0.1

Type RM Length L Ch R = 1 ,41498.51,249.522600,249.522600,249.522600
XS GIS Cut Line= 6
652539.161224566762637.962396579652375.020720447762783.816323451
652279.185787545762885.477992977652192.066669092763002.233816254
652094.683224974763146.875645742652003.649032865763260.082170701
#Sta/Elev= 30
9490.806821.49049509.121822.72669535.558827.23559561.994825.30259575.212821.7487
9601.649808.73959623.811800.43239653.265786.91129655.971786.30379682.719789.0171
9697.446788.65749738.944783.23969754.225775.47049767.428764.43459782.313756.3421
9796.047751.16969875.082710.40349922.004677.47129939.218656.48159950.164647.8678
 9962.45642.12219974.736639.679910008.57638.382410023.35 640.35510047.46641.1198
10180.42674.372410219.88690.134610256.22 708.60910295.56725.863310315.62732.9085
#Mann= 3 , 0 , 0
9490.806    0.04       09490.806    0.04       010315.62    0.04       0
#XS Ineff= 2 , 0
       0                               0
Bank Sta=9490.806,10315.62
Exp/Cntr=0.3,0.1

Type RM Length L Ch R = 1 ,41248.98,249.522600,249.522600,249.522600
XS GIS Cut Line= 6
652187.611713454762744.601236639 652102.37160713762798.954992637
651924.950901292762879.088101399651868.170224258762921.516641339
651782.810080583763013.587460163651689.744123109763148.988830206
#Sta/Elev= 30
9796.853689.61289832.412682.91399848.751674.93639871.876666.01249917.227655.6486
9928.272651.30799939.317644.28839950.059640.40159982.237636.2342    9999638.5588
10047.63636.626810081.56643.054310103.51651.250310129.42668.670310137.55676.5022
10153.49700.853410163.88711.564710181.95726.977110195.68733.669610224.74751.6066
10239.32758.998310265.37768.054610286.16 773.09210302.63779.468610336.06781.7293
10341.26784.617710365.54790.779410389.44 788.20210437.24793.781510453.95797.0936
#Mann= 3 , 0 , 0
9796.853   0.055       09796.853   0.055       010453.95   0.055       0
#XS Ineff= 2 , 0
       0                               0
Bank Sta=9796.853,10453.95
Exp/Cntr=0.3,0.1

Type RM Length L Ch R = 1 ,40999.46,249.522600,249.522600,249.522600
XS GIS Cut Line= 6
652258.247784486762219.742569385651945.646485159762599.636078073
651916.798316158762628.897067892651876.425853997762658.367264034
651857.503618479762679.960690981651633.476868446763066.180417689
#Sta/Elev= 30
9443.045754.30799463.173755.18329489.558752.27589515.943754.79479529.135753.4029
9555.279761.97779581.234764.63069634.135783.60029659.099788.03259684.903784.9745
9774.869752.25659792.812749.9761 9824.65736.57669877.687693.66999916.244652.5541
9929.096642.2698 9956.63629.55149970.672628.475310003.63630.305210034.95629.3962
10043.47631.686910059.67643.856910221.51713.171510315.49760.680310336.84763.9252
 10355.9779.810610385.52791.656210454.57825.688910477.58832.820310501.49834.5378
#Mann= 3 , 0 , 0
9443.045  0.0578       09443.045  0.0578       010501.49  0.0578       0
#XS Ineff= 2 , 0
       0                               0
Bank Sta=9443.045,10501.49
Exp/Cntr=0.3,0.1

Type RM Length L Ch R = 1 ,40749.94,249.522600,249.522600,249.522600
XS GIS Cut Line= 6
651739.294607879762440.856267772 651702.11817533762560.838450014
651686.040491815762598.022108494651685.166258105762599.820917939
651650.685787062762679.527797847651548.120113325762942.772732291
#Sta/Elev= 30
 9832.88661.27039858.156655.22919879.094646.36749910.501637.09519941.908629.2825
9952.377625.51919973.918622.57429984.813619.49639995.707618.631410017.54619.6606
10028.43621.981610039.33626.167210050.23639.313410061.12 656.10110072.02665.2251
10076.98668.629610115.18689.930310131.05  699.6810168.84721.147410190.31736.6197
10201.04 736.76510211.77740.0667 10222.5750.592510243.97 768.63410265.43783.4564
10308.36808.770510319.09816.206110329.83 824.78410362.02846.291910370.37 851.165
#Mann= 3 , 0 , 0
 9832.88   0.055       0 9832.88   0.055       010370.37   0.055       0
#XS Ineff= 2 , 0
       0                               0
Bank Sta=9832.88,10370.37
Exp/Cntr=0.3,0.1

Type RM Length L Ch R = 1 ,40500.42,249.522600,249.522600,249.522600
XS GIS Cut Line= 6
651694.583514477761987.184584889651651.789903144762073.310151508
 651418.50293285762587.444960841651378.914154933762689.280326272
651351.067586351762780.155247612651328.935000496762882.417411369
#Sta/Elev= 30
9435.788709.14149444.515 710.2229478.014706.91399500.347707.30749531.959701.2445
9555.817 708.1019588.816713.66939621.815711.95559665.814701.50879698.812691.4036
9797.809654.38639907.805635.36729929.804633.06319940.804627.10219984.716617.5076
 10017.5 618.25410028.42620.551210055.34633.130510072.07646.756310093.89668.4088
10104.66677.401510115.39684.261710169.04723.5648 10190.5742.014610201.23743.5469
 10211.8749.431410222.26760.513210326.95 843.17810377.66880.842510405.53897.9095
#Mann= 3 , 0 , 0
9435.788  0.0405       09435.788  0.0405       010405.53  0.0405       0
#XS Ineff= 2 , 0
       0                               0
Bank Sta=9435.788,10405.53
Exp/Cntr=0.3,0.1

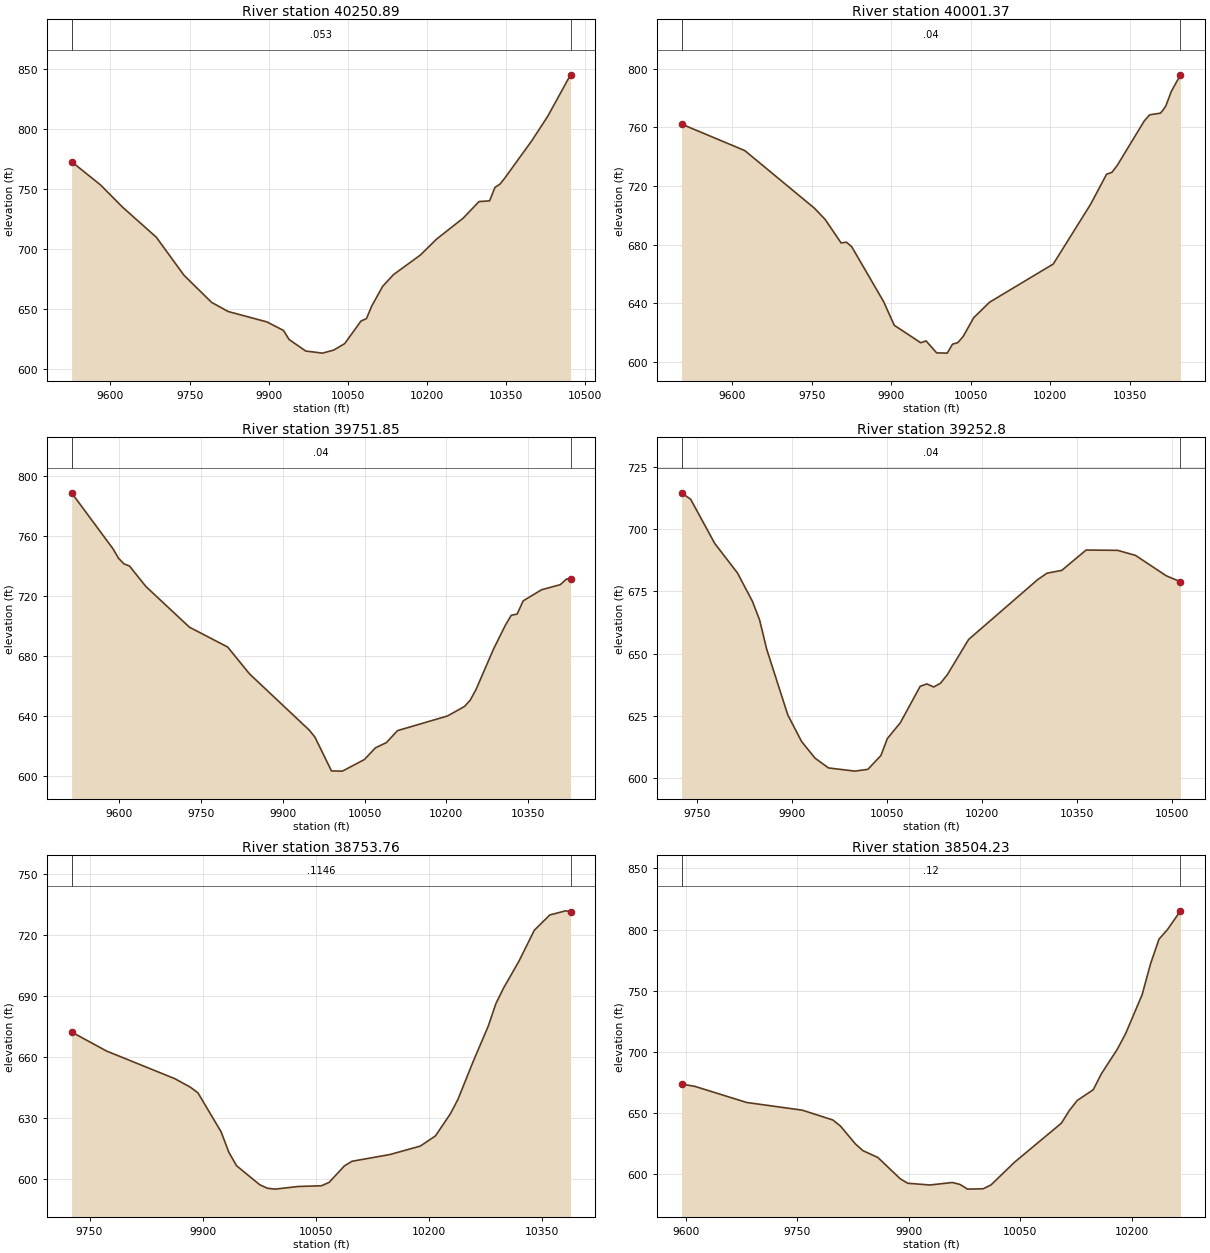
Type RM Length L Ch R = 1 ,40250.89,249.522600,249.522600,249.522600
XS GIS Cut Line= 6
651385.742200911761933.745972406651333.970552891762078.582394542
651224.436749151762418.966082266651208.098746789762485.247586375
651172.463621308762707.012672108651169.217784564762848.165564026
#Sta/Elev= 30
9526.405772.89919581.159753.58899623.519734.82779686.958710.01749739.387678.3533
9791.815655.72999823.272648.11619896.673639.4631 9928.13632.34289938.616 624.846
9970.219615.206910002.03613.469810023.11615.982810044.04621.382310074.94640.1951
10085.24642.185510095.54652.857210116.05669.083710136.46678.813810187.49695.1536
10217.89708.300410268.43725.800710298.63739.686610318.76740.304910328.83751.4674
10338.86754.407310348.87760.054410398.96790.518610428.96810.739210472.15845.2592
#Mann= 3 , 0 , 0
9526.405   0.053       09526.405   0.053       010472.15   0.053       0
#XS Ineff= 2 , 0
       0                               0
Bank Sta=9526.405,10472.15
Exp/Cntr=0.3,0.1

Type RM Length L Ch R = 1 ,40001.37,249.522600,249.522600,249.522600
XS GIS Cut Line= 6
651047.086475088 761887.75568864651013.093430984762073.430825228
651000.200496435762177.196527716650988.158124888762384.895932748
 651000.84407183762652.539426583651032.788270821762821.714944016
#Sta/Elev= 30
9504.047762.13489623.475744.05689754.892704.77729775.046697.16939805.243681.0816
9815.276681.6186 9825.31678.5003 9885.51 641.0749905.576624.95479955.605613.0207
 9965.61614.2893 9985.62606.121610005.63605.951410015.63612.073510025.63613.1229
10035.63617.306510055.63630.131410085.64640.707810205.76666.705110276.11707.3616
10306.42727.928510316.52729.229810326.62734.0002 10377.5 764.24510387.69768.4497
10408.13769.593510412.98771.6805 10418.4774.622110428.67784.412710445.91795.7208
#Mann= 3 , 0 , 0
9504.047    0.04       09504.047    0.04       010445.91    0.04       0
#XS Ineff= 2 , 0
       0                               0
Bank Sta=9504.047,10445.91
Exp/Cntr=0.3,0.1

Type RM Length L Ch R = 1 ,39751.85,499.045100,499.045100,499.045100
XS GIS Cut Line= 6
650743.845665421761889.297794822650732.171295531762254.204358184
650750.199626447762462.751278001650763.769254299762544.024596599
650792.358620626762643.246891264650859.945650183762781.390085687
#Sta/Elev= 30
9513.184788.75759589.102751.4976 9599.13745.24399609.138741.47099619.143740.1046
 9649.16 726.4719729.205699.31719799.221686.12129839.221668.26789949.298630.6391
9959.309626.07089989.432603.670110009.55603.538210049.84611.270410069.99619.0416
10090.15622.539210110.43630.4866 10202.2640.258810233.29646.586110243.83650.8229
10254.37657.864210286.35684.697310308.04700.557510318.88707.250710329.72708.0633
10340.83  716.8710374.51 724.24710408.82727.644410420.26731.400910427.57731.4222
#Mann= 3 , 0 , 0
9513.184    0.04       09513.184    0.04       010427.57    0.04       0
#XS Ineff= 2 , 0
       0                               0
Bank Sta=9513.184,10427.57
Exp/Cntr=0.3,0.1

Type RM Length L Ch R = 1 , 39252.8,499.045200,499.045200,499.045200
XS GIS Cut Line= 6
650054.362282744762393.799152878650103.900512215762433.463230871
650183.193812766762478.974445152650457.347547641762570.578306422
650543.949950168 762626.81271501650728.792970665762779.824803132
#Sta/Elev= 30
9725.372714.64449739.822712.03879777.758694.30449813.736682.4087 9837.28671.0294
9848.697663.49319859.941651.69889893.255625.29849915.036614.60149936.299 607.909
9957.486603.98899999.115602.697410019.74603.416310040.26608.953610050.52615.8119
10071.05622.172410102.35636.816210112.98637.783110123.73636.542510134.48638.0601
10145.39641.536110178.83655.640610287.72679.676610302.77682.325910326.09683.4608
10364.46691.6234 10414.3691.511610442.58689.478210490.88681.307410513.59 678.848
#Mann= 3 , 0 , 0
9725.372    0.04       09725.372    0.04       010513.59    0.04       0
#XS Ineff= 2 , 0
       0                               0
Bank Sta=9725.372,10513.59
Exp/Cntr=0.3,0.1

Type RM Length L Ch R = 1 ,38753.76,249.522600,249.522600,249.522600
XS GIS Cut Line= 6
650038.723476119763039.435076942650142.002967966763036.912997042
650403.287023916762984.149882278650508.391192161762973.697876324
650599.372040596762979.221900388650691.257631804763001.194721136
#Sta/Elev= 30
9726.198672.26899772.544662.93289863.147649.32779883.525645.1893 9893.76642.3767
9924.464   623.29934.699613.19049944.934606.54289975.638597.21339985.873595.4626
9996.108595.033910026.86596.337110057.39596.689610067.57598.313210087.92606.4345
10098.08608.734910148.53612.064610188.63 616.20310208.66621.194810228.66632.1522
10238.66639.276710258.74657.780210278.83675.274110288.88686.251710299.02693.8799
10319.44  707.1110339.85722.341710360.41729.8517 10381.3731.871810387.84731.4605
#Mann= 3 , 0 , 0
9726.198  0.1146       09726.198  0.1146       010387.84  0.1146       0
#XS Ineff= 2 , 0
       0                               0
Bank Sta=9726.198,10387.84
Exp/Cntr=0.3,0.1

Type RM Length L Ch R = 1 ,38504.23,499.045200,499.045200,499.045200
XS GIS Cut Line= 6
650000.639051054763125.011312241650063.556728647763165.400887047
650139.680569731763195.726761874650371.798035787763226.333684093
650548.158155385763288.289369293650629.973656711763331.169428735
#Sta/Elev= 30
9594.364673.80199612.243671.91549681.888658.76429756.739652.46499797.787644.4712
 9808.05639.54249828.281624.84239838.352619.38569858.493613.7826 9888.53596.4244
9898.541592.74469928.574591.32019958.766593.36959968.962591.76019979.158587.9416
10000.12588.221810010.66591.385310042.22609.890210105.34641.825610115.98652.1215
10126.73660.427310148.21669.179110158.95     68210180.64 702.32310191.69714.9345
10213.93746.739710225.29 772.06910236.65792.1742   10248799.992710265.54815.3564
#Mann= 3 , 0 , 0
9594.364    0.12       09594.364    0.12       010265.54    0.12       0
#XS Ineff= 2 , 0
       0                               0
Bank Sta=9594.364,10265.54
Exp/Cntr=0.3,0.1

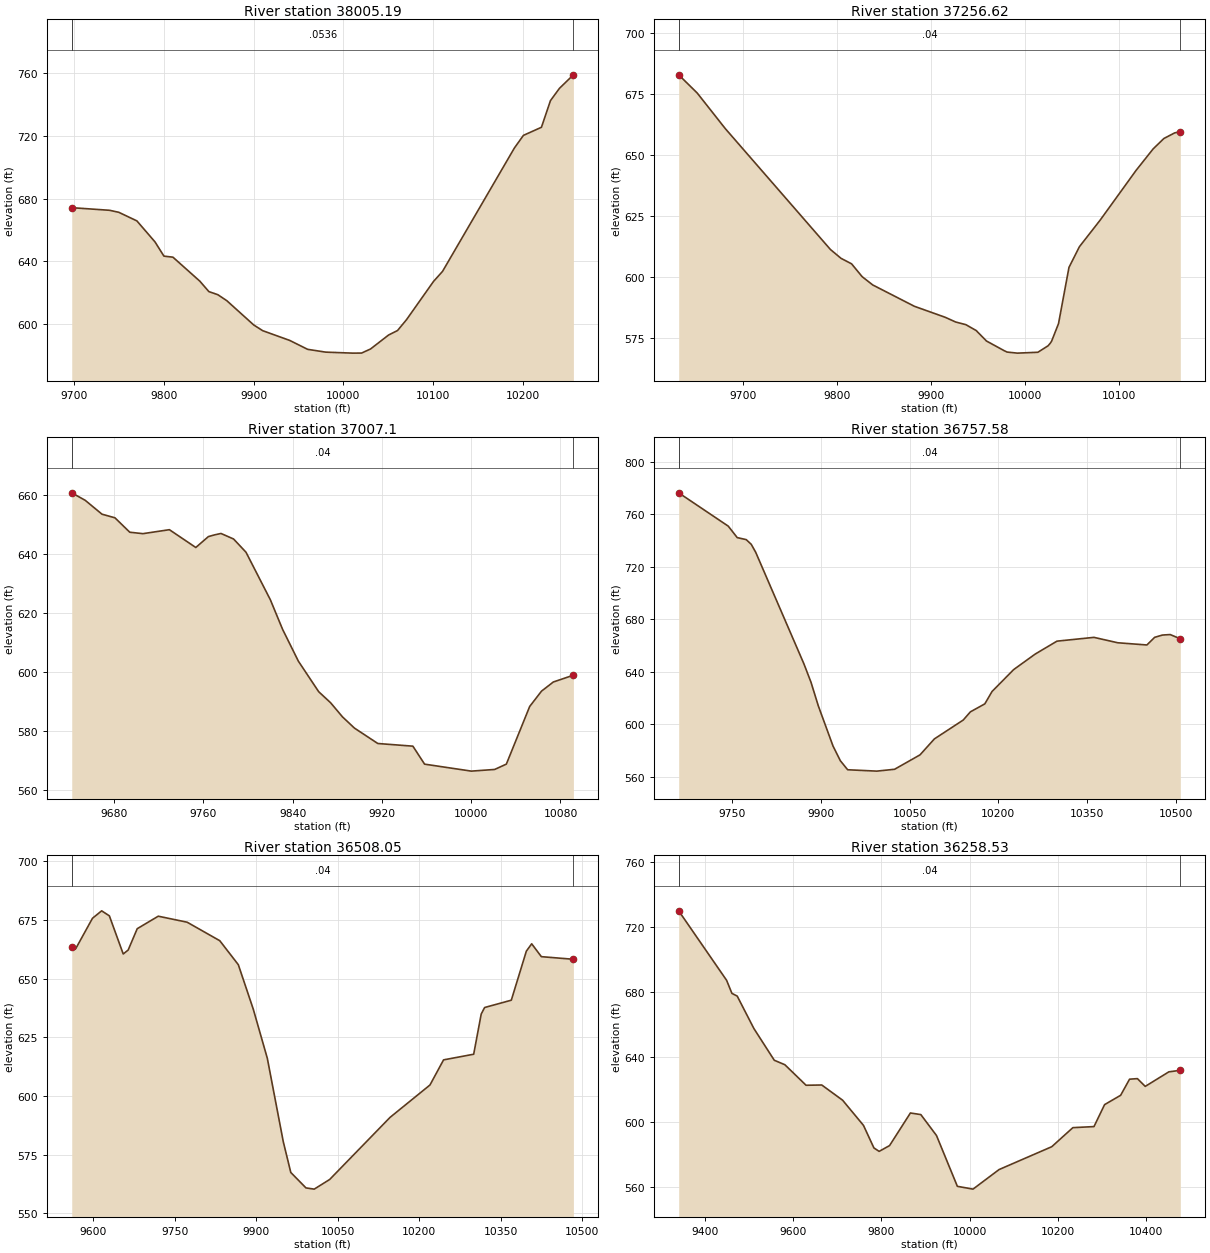
Type RM Length L Ch R = 1 ,38005.19,748.567800,748.567800,748.567800
XS GIS Cut Line= 6
649964.034374227763153.990014726649976.263000302763206.419900201
649981.206625592763249.141510647649983.495678579763314.020736161
649979.386702013763453.838577284649962.534305468763710.441955068
#Sta/Elev= 30
 9697.32674.16419739.459672.49129749.717671.21559769.877665.75019790.011652.4086
9800.042643.30149810.048642.64319840.067627.33859850.073620.72439860.079 618.742
 9870.08614.92719900.083 599.4579910.085595.81979940.088589.64659960.109583.9518
9980.136582.174410010.18581.5366 10020.2581.578610030.22584.182710050.25593.0485
10060.27595.940110070.29602.850310100.34627.183210110.36 633.557 10190.5712.2018
10200.52720.214310220.58725.356810230.63742.320410240.67750.167410256.18758.7616
#Mann= 3 , 0 , 0
 9697.32  0.0536       0 9697.32  0.0536       010256.18  0.0536       0
#XS Ineff= 2 , 0
       0                               0
Bank Sta=9697.32,10256.18
Exp/Cntr=0.3,0.1

Type RM Length L Ch R = 1 ,37256.62,249.522600,249.522600,249.522600
XS GIS Cut Line= 6
 649753.71089372762820.594248995649727.940257341762847.497367978
649642.420391321762907.369730443649566.584920168762946.630001858
649339.046077639 763050.51720196649289.707108825763077.760112375
#Sta/Elev= 30
9631.877682.90739651.581675.44549681.454 660.841 9793.32611.23769804.581607.6127
9815.841605.34769827.102600.07449838.362596.67959882.726587.91479915.565583.3986
9926.511581.48189937.457580.38289948.403577.98379959.349 573.6849978.031569.7468
9981.242569.14779992.188568.707610014.05569.057210024.98571.734410027.47572.9031
10028.67573.626810036.02580.811610047.13603.872810058.23612.366610080.44623.3446
10118.53 643.68710136.73652.528910148.15656.786310159.57659.076610165.62659.5956
#Mann= 3 , 0 , 0
9631.877    0.04       09631.877    0.04       010165.62    0.04       0
#XS Ineff= 2 , 0
       0                               0
Bank Sta=9631.877,10165.62
Exp/Cntr=0.3,0.1

Type RM Length L Ch R = 1 , 37007.1,249.522500,249.522500,249.522500
XS GIS Cut Line= 6
 649683.67296356 762610.80101651649640.572317511762648.174461812
649596.790703326762676.285946861 649558.66659832 762696.19582884
649466.372433096 762733.83699429649278.061577648762793.840858147
#Sta/Elev= 30
9642.034 660.6769654.043658.15329669.155 653.4349680.744652.21129694.031647.3244
9705.767646.83699729.535648.18359753.195642.15129764.477645.84489769.999646.4205
9775.758646.9016 9787.04645.0325 9798.19640.54219820.038624.41119830.962614.4212
9845.118603.6274 9863.32593.27779874.001589.52999884.682584.73339895.336580.9516
9916.293575.72119947.729574.81889958.208568.723110000.12566.358910021.02566.9245
10031.48568.734710052.41 588.27810063.01593.469910073.61596.572910091.56598.8654
#Mann= 3 , 0 , 0
9642.034    0.04       09642.034    0.04       010091.56    0.04       0
#XS Ineff= 2 , 0
       0                               0
Bank Sta=9642.034,10091.56
Exp/Cntr=0.3,0.1

Type RM Length L Ch R = 1 ,36757.58,249.522600,249.522600,249.522600
XS GIS Cut Line= 6
649524.819386064762326.697502968649477.023882629762374.110159226
 649385.49019882762449.690864525649022.041147908762707.188333599
648954.790537541762757.719809282648851.909330208762842.732915481
#Sta/Elev= 30
9659.034776.34839742.932750.94899758.139742.21169773.347740.67179781.836737.1047
9789.388731.03979870.921646.07959882.972631.97759895.391613.9199 9920.23583.3595
9932.649572.12959945.069 565.2259994.368564.185110024.48 565.59510067.51576.5766
10091.89588.761810140.66603.126410152.85609.396710177.23615.459310189.42624.8879
10225.99641.569310262.57653.452910299.36663.269210361.91666.160410402.31662.0374
10451.55660.355310464.69666.183610477.82667.918510490.96 668.29710508.15665.0781
#Mann= 3 , 0 , 0
9659.034    0.04       09659.034    0.04       010508.15    0.04       0
#XS Ineff= 2 , 0
       0                               0
Bank Sta=9659.034,10508.15
Exp/Cntr=0.3,0.1

Type RM Length L Ch R = 1 ,36508.05,249.522600,249.522600,249.522600
XS GIS Cut Line= 6
649387.612204578762019.193043086649342.563026658762080.495383427
649285.535304674762150.430648614 649206.74458959762239.255605847
648925.410830348762526.982479771648762.923570209762698.511896281
#Sta/Elev= 30
9560.056663.54149567.262662.78489598.241675.78839615.128678.96549629.311676.8365
9654.846660.57419663.922662.23899680.653671.35279719.363676.6757 9772.58674.1123
9832.664666.22649866.828 655.9969894.423636.97439920.206616.10199949.613580.5263
9963.411567.43779991.391560.848710006.58560.3323   10035 564.438 10146.2590.9138
 10219.7604.718510244.74615.432710300.21 617.83510314.07634.960810320.36637.7495
10369.49640.8659 10397.2661.779410407.04664.912510424.81659.425810483.82658.3115
#Mann= 3 , 0 , 0
9560.056    0.04       09560.056    0.04       010483.82    0.04       0
#XS Ineff= 2 , 0
       0                               0
Bank Sta=9560.056,10483.82
Exp/Cntr=0.3,0.1

Type RM Length L Ch R = 1 ,36258.53,499.045200,499.045200,499.045200
XS GIS Cut Line= 6
 649260.95549433761645.873118344649218.575578109761705.559539385
 649096.32866993761890.312847849648856.157429317762272.936719569
648740.864406407762449.158553687648639.507354413762596.129859548
#Sta/Elev= 30
9341.378729.76419449.882687.07669461.873679.06119473.864677.3851 9511.67657.4426
  9557.8637.97029581.782635.21279629.746622.60659665.263622.7706 9712.49613.4281
9759.716597.96719783.329  584.129795.136581.99269818.749585.54989865.976605.5822
9889.589604.57689925.009591.74149972.235560.529810007.66558.803610066.69570.8258
10185.94584.857810233.74596.565810281.54597.223210305.53610.716510341.85616.4422
10362.08626.347510379.82626.679910397.56621.917510451.12630.8635   10477631.7812
#Mann= 3 , 0 , 0
9341.378    0.04       09341.378    0.04       0   10477    0.04       0
#XS Ineff= 2 , 0
       0                               0
Bank Sta=9341.378,10477
Exp/Cntr=0.3,0.1

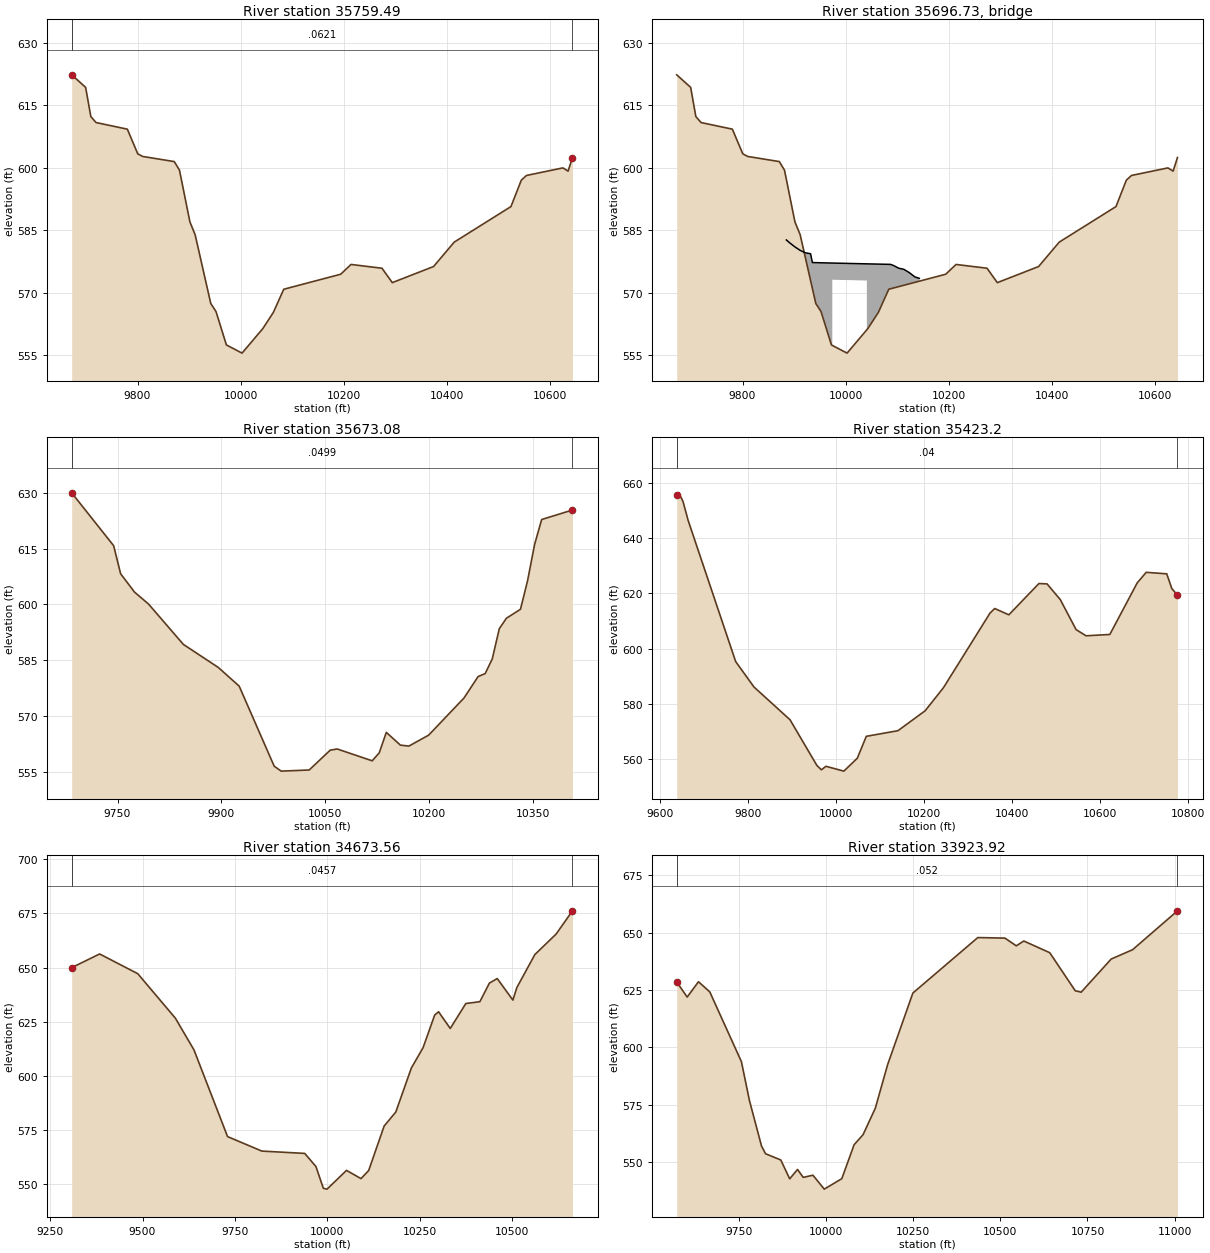
Type RM Length L Ch R = 1 ,35759.49,86.404800,86.404800,86.404800
XS GIS Cut Line= 4
648484.908082157761708.291460246648420.335068345762149.831257254
648415.099418581762579.154538155648427.315934718762673.396233946
#Sta/Elev= 30
9672.399622.30669699.391619.30259709.498612.28789719.604610.85889780.242 609.271
9800.455603.35219809.975602.7245  9871.2601.49399881.306599.43769901.519587.0214
9911.625583.96479941.944567.45259952.051565.52899972.263557.506910002.58555.5404
10043.01561.452910063.22565.302910083.43570.865410193.81574.469610213.81 576.814
10273.82575.907410293.82572.451510373.82576.318210413.83582.172210523.83 590.702
10543.84597.021610553.88598.163510624.47599.978310634.55599.204610643.02602.4699
#Mann= 3 , 0 , 0
9672.399  0.0621       09672.399  0.0621       010643.02  0.0621       0
#XS Ineff= 2 , 0
       0                10087.48       0
Bank Sta=9672.399,10643.02
Exp/Cntr=0.3,0.1

Type RM Length L Ch R = 3 ,35696.73,,,
BEGIN DESCRIPTION:
END DESCRIPTION:
Bridge Culvert--1,0,-1,-1, 0
Deck Dist Width WeirC Skew NumUp NumDn MinLoCord MaxHiCord MaxSubmerge Is_Ogee
30.702400,25.000000,2.6,0, 20, 20, , , 0.95, 0, 0,0,,
 9884.92 9891.31 9901.44 9911.57 9921.70 9931.83 9935.32 9973.93 9973.9310040.93
10040.9310086.9210092.8010102.8110111.9410112.8210113.3610123.3810133.9610142.66
  582.69  582.00  581.03  580.20  579.61  579.39  577.27  577.15  577.15  576.96
  576.96  576.83  576.55  575.91  575.67  575.63  575.59  574.84  573.83  573.48
 -417.31 -418.00 -418.97 -419.80 -420.39 -420.61 -422.73 -422.85  573.15  572.96
 -423.04 -423.17 -423.45 -424.09 -424.33 -424.37 -424.41 -425.16 -426.17 -426.52
 9884.92 9891.31 9901.44 9911.57 9921.70 9931.83 9935.32 9977.74 9977.7410044.74
10044.7410086.9210092.8010102.8110111.9410112.8210113.3610123.3810133.9610142.66
  582.69  582.00  581.03  580.20  579.61  579.39  577.27  577.14  577.14  576.95
  576.95  576.83  576.55  575.91  575.67  575.63  575.59  574.84  573.83  573.48
 -417.31 -418.00 -418.97 -419.80 -420.39 -420.61 -422.73 -422.86  573.14  572.95
 -423.05 -423.17 -423.45 -424.09 -424.33 -424.37 -424.41 -425.16 -426.17 -426.52
BR Coef=-1 , 0 , 0 ,, 0 ,,,0.8,0,1,0,
WSPro=,,,, 1 ,,,, 0 ,,,, 0 ,,,,-1 ,-1 ,-1 , 0 , 0 , 0 , 0 , 0
BC Design=,, 0 ,, 0 ,,,,,,

Type RM Length L Ch R = 1 ,35673.08,249.879500,249.879500,249.879500
XS GIS Cut Line= 4
648390.666386336761704.801027074  648367.9785707761910.736584574
648334.819455504762137.614741147648278.972524732762418.594611973
#Sta/Elev= 30
9683.812629.97479744.375615.78039754.436608.25239774.557603.31729794.678600.1312
 9844.98589.29649895.302 583.1189925.621578.08519976.152556.58929986.259555.2708
10026.68555.5745   10057560.893710067.11561.217910117.64558.039910127.81560.1829
10138.01565.6701 10158.4 562.24710170.65561.998610199.18564.934710250.16574.8986
10270.55580.659910280.75581.457910290.94585.375410301.14593.493810311.33596.2974
10331.72598.720410341.92606.361810352.12616.127810362.31622.806710406.76625.3661
#Mann= 3 , 0 , 0
9683.812  0.0499       09683.812  0.0499       010406.76  0.0499       0
#XS Ineff= 2 , 0
       0                10095.33       0
Bank Sta=9683.812,10406.76
Exp/Cntr=0.3,0.1

Type RM Length L Ch R = 1 , 35423.2,749.638700,749.638700,749.638700
XS GIS Cut Line= 6
648207.319709251761632.708375859648147.714711733761775.697083435
648090.489658899762054.358027384648029.548799886762279.603523804
647940.834869348762493.575539259647827.960238245762695.913866186
#Sta/Elev= 30
9638.685655.79639643.271656.55849652.934653.44049664.526646.57119772.558595.2543
9814.053 586.0399895.899574.14059957.035557.51679967.225555.94319977.414557.2301
10018.18555.470610048.77560.173210069.16568.1117   10141570.1557 10202.8577.4038
10244.36585.780810350.02612.871210360.71614.537910392.79612.251910461.14623.6172
10479.61623.4742 10509.6617.768410545.52606.869110568.03604.633210622.07605.1047
10684.31623.854210704.66627.680910751.31627.137410762.98621.734210775.71619.4334
#Mann= 3 , 0 , 0
9638.685    0.04       09638.685    0.04       010775.71    0.04       0
#XS Ineff= 2 , 0
       0                               0
Bank Sta=9638.685,10775.71
Exp/Cntr=0.3,0.1

Type RM Length L Ch R = 1 ,34673.56,749.638600,749.638600,749.638600
XS GIS Cut Line= 6
648147.099626912761536.157746166647946.812531082761590.998895991
647714.223526824761625.112017326647546.671633602761678.371431443
647398.967603829761700.679649904646843.809171477761891.049504464
#Sta/Elev= 30
9308.339649.96789383.939656.2883  9487.2647.17079588.944626.63199639.415611.9364
9730.265571.88479823.045565.18929939.115564.11469969.531558.05659989.588547.9916
9999.615547.605910052.32556.276310091.48552.462310112.32556.203310154.15576.7535
10185.73583.240610227.84603.577210259.42612.9254   10291628.064610301.53629.5781
10333.11 621.85410375.32633.384410413.36634.239610439.03642.806910460.27644.9273
10502.74634.983710513.36640.726110562.04655.987910619.86665.507410663.98676.2252
#Mann= 3 , 0 , 0
9308.339  0.0457       09308.339  0.0457       010663.98  0.0457       0
#XS Ineff= 2 , 0
       0                               0
Bank Sta=9308.339,10663.98
Exp/Cntr=0.3,0.1

Type RM Length L Ch R = 1 ,33923.92,249.879600,249.879600,249.879600
XS GIS Cut Line= 6
648233.653969802 761357.24611712648143.086346084761323.135872873
647763.470278525761127.801693104647419.109302143760922.197963206
647155.841036349760833.279912076646927.851107921760792.151653742
#Sta/Elev= 30
 9572.26628.52969602.224621.93229634.648628.62229667.072624.18939757.794593.7593
9780.857 576.7789815.451556.97729826.982553.63539870.653550.92499896.171542.6987
9918.636546.78329935.005543.3364 9962.81544.28019995.296538.216110045.57 542.772
10080.87 557.56810106.48561.9341 10141.7573.509910176.99592.480710249.37623.6892
10435.53647.870810513.34647.637410545.82644.271910567.48646.365710641.79641.2746
10714.96624.677210732.01624.068210818.03638.518210879.34642.575911008.07659.5263
#Mann= 3 , 0 , 0
 9572.26   0.052       0 9572.26   0.052       011008.07   0.052       0
#XS Ineff= 2 , 0
       0                               0
Bank Sta=9572.26,11008.07
Exp/Cntr=0.3,0.1