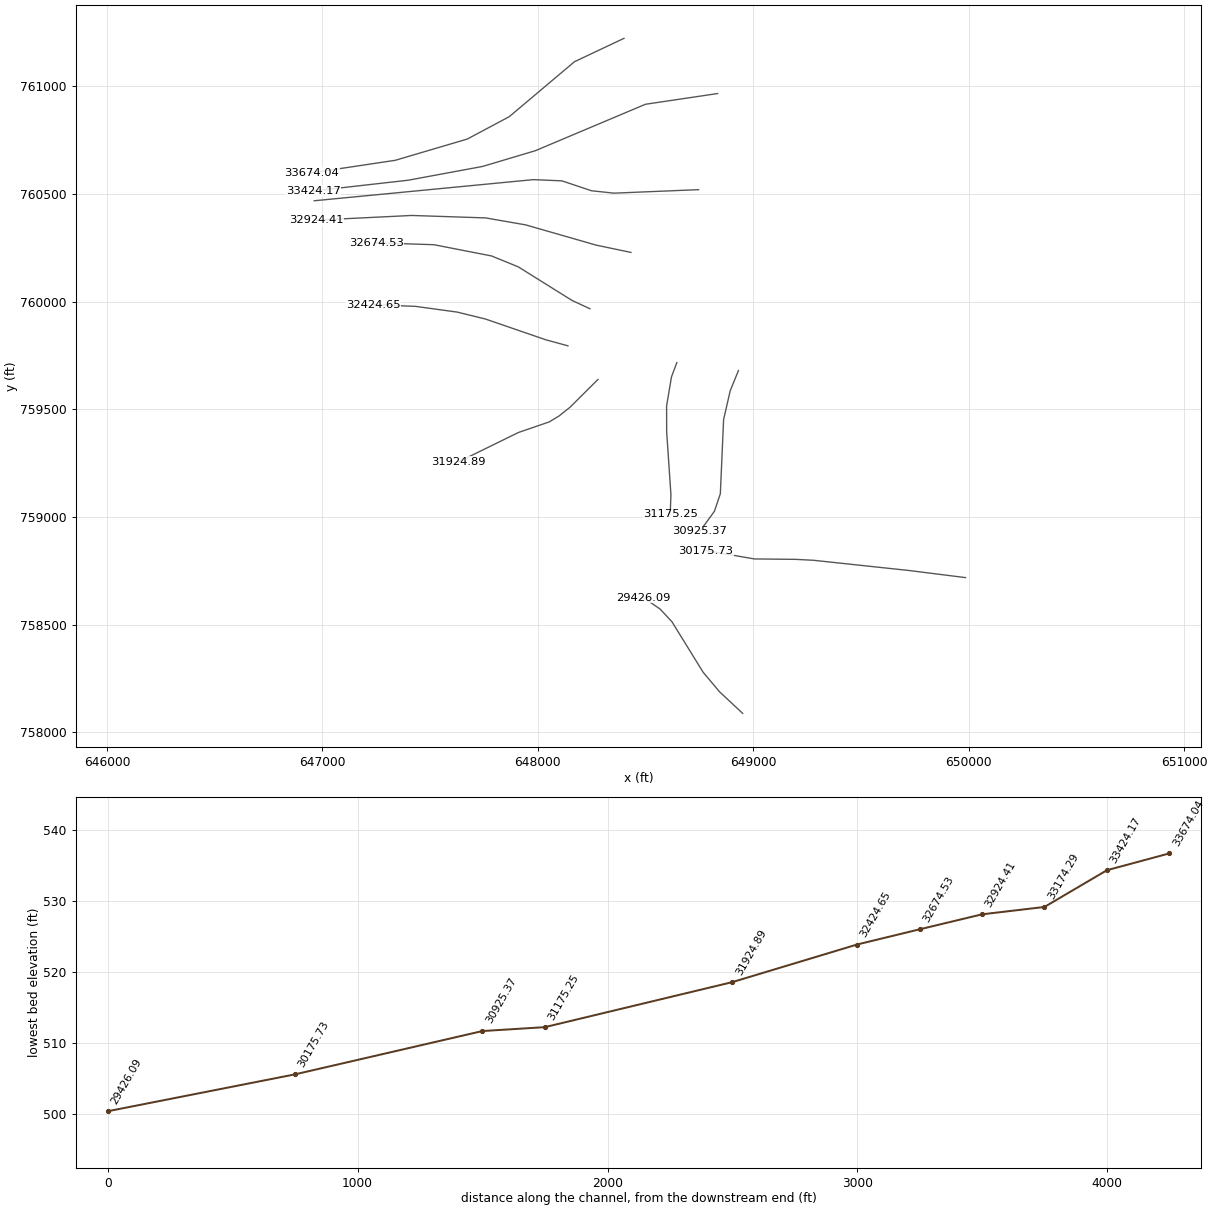
HEC-RAS study 3382_ras.prj: 3382

--- 3382_ras.g01 (geometry) --- (continued)

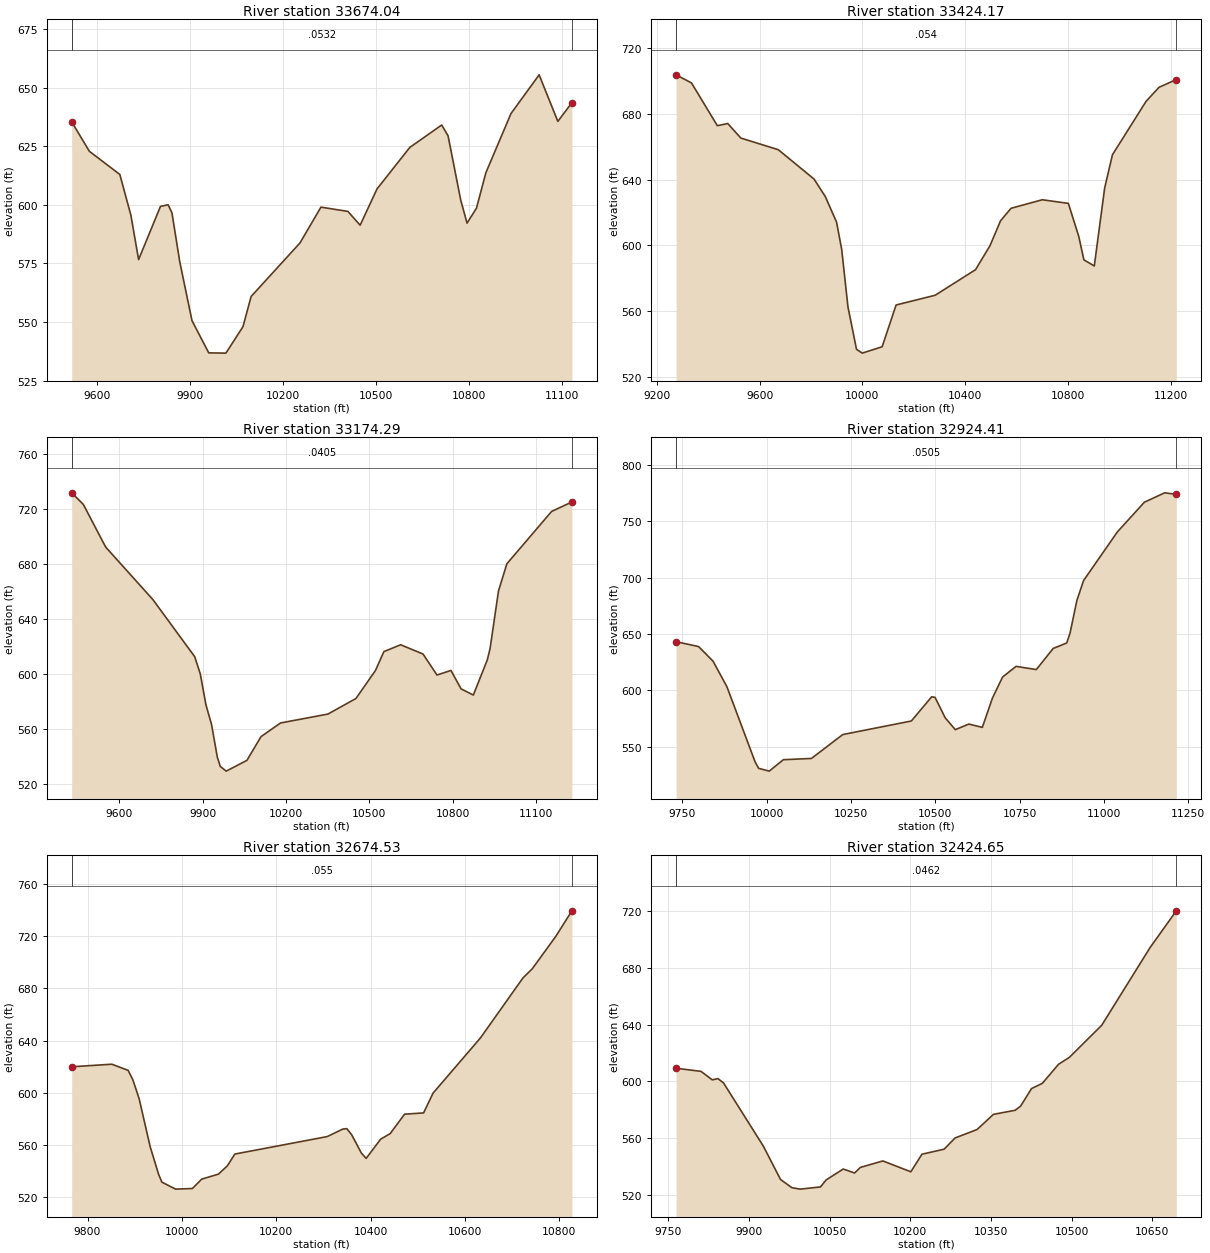
Type RM Length L Ch R = 1 ,33674.04,249.879500,249.879500,249.879500
XS GIS Cut Line= 6
648400.277034613761222.578160623648170.268722358761113.937186321
647867.496690756760858.787174407647672.883190256 760755.05956994
647338.552795206760656.329346053646949.883610132760598.069874133
#Sta/Elev= 30
9518.266635.48419575.456622.85349673.744612.97899709.476595.57579734.384 576.618
9804.973599.33279829.709600.03799842.078596.55599867.306575.67529906.779550.5544
9960.865536.810510016.33536.694910071.31547.9698 10097.7560.874910255.57583.7559
10323.23599.021110410.24597.201910449.69591.308710504.19606.794410610.05624.5119
10713.07634.0929 10733.6 629.48810774.44602.061110794.85592.204710825.29598.5616
10855.74613.7292 10936.8638.979611027.66  655.5111088.08635.624611133.43643.6222
#Mann= 3 , 0 , 0
9518.266  0.0532       09518.266  0.0532       011133.43  0.0532       0
#XS Ineff= 2 , 0
       0                               0
Bank Sta=9518.266,11133.43
Exp/Cntr=0.3,0.1

Type RM Length L Ch R = 1 ,33424.17,249.879500,249.879500,249.879500
XS GIS Cut Line= 6
648834.850871292760966.296906888648499.981043763760916.492231779
647988.838600684760700.913064817647744.011837726760627.904684473
647398.300736987760563.861071552646957.793764998760514.024478552
#Sta/Elev= 30
9275.292  703.949335.192699.00769435.702672.94949476.239674.25979527.206665.3958
9672.741658.31599811.706640.44899855.487629.80939899.441614.1658 9919.46597.5342
9943.823562.4717 9977.11536.65179999.301534.326310076.76538.204910131.05563.6605
10283.08569.599610440.12 585.18310496.41599.848810537.27614.960510578.13622.5986
10699.83627.800810801.09625.587610841.46 605.51510861.64591.164810902.01587.4578
10942.37634.995710972.57655.207211103.33687.765211153.59696.306111220.99701.0749
#Mann= 3 , 0 , 0
9275.292   0.054       09275.292   0.054       011220.99   0.054       0
#XS Ineff= 2 , 0
       0                               0
Bank Sta=9275.292,11220.99
Exp/Cntr=0.3,0.1

Type RM Length L Ch R = 1 ,33174.29,249.879600,249.879600,249.879600
XS GIS Cut Line= 6
 648746.62338252760520.063890418648353.860168542760503.814613207
648249.629575234760514.902188168648112.327390742 760560.91084953
647979.711972244760566.633236067646962.078187078760468.502493873
#Sta/Elev= 30
 9429.33731.64269471.175723.24419551.405692.23169721.597653.90729871.771612.4396
9891.838599.90779912.063577.48379932.414  563.029953.041539.36069963.556532.6385
 9985.04529.160810059.62537.005510110.32554.283810180.43564.195910350.91570.6785
10451.44581.986910521.83602.382110551.99616.089310612.32621.100510692.76614.3606
10743.04599.090610793.32602.4106 10829.6 589.00110873.76584.523910924.03 610.127
10934.09618.507710964.23660.275910994.35680.018111154.95718.049411228.13725.0058
#Mann= 3 , 0 , 0
 9429.33  0.0405       0 9429.33  0.0405       011228.13  0.0405       0
#XS Ineff= 2 , 0
       0                               0
Bank Sta=9429.33,11228.13
Exp/Cntr=0.3,0.1

Type RM Length L Ch R = 1 ,32924.41,249.879500,249.879500,249.879500
XS GIS Cut Line= 6
648432.472958823760228.694669499648271.779221271760262.372012666
647943.551757599760356.575676529647758.042251884760388.884812876
647415.162051337 760400.29384447 646970.54788014760378.512004946
#Sta/Elev= 30
9731.803643.1239 9798.49638.80559841.345625.8313  9882.5603.09239965.979 536.375
9976.442530.611810007.82528.1212 10049.8538.2779   10133539.380310225.89560.6107
10429.15572.667610489.42594.167910499.46593.653310529.49575.534110559.52564.9752
10599.56  569.9410639.58566.990910669.58593.047410699.58611.715410739.58621.2156
10799.61618.362810849.65637.126610889.68641.979910899.69650.856310919.71679.6346
10939.72697.477111039.87740.674511119.99767.090311180.07775.414811214.58774.0951
#Mann= 3 , 0 , 0
9731.803  0.0505       09731.803  0.0505       011214.58  0.0505       0
#XS Ineff= 2 , 0
       0                               0
Bank Sta=9731.803,11214.58
Exp/Cntr=0.3,0.1

Type RM Length L Ch R = 1 ,32674.53,249.879600,249.879600,249.879600
XS GIS Cut Line= 6
648242.266881097759967.161312636648158.300023088760006.158049387
647909.300387764760161.756135214647785.292522972760212.306936035
647518.037774674760264.463197999647251.218279729760273.184461852
#Sta/Elev= 30
 9766.45619.87559851.572621.84279886.138617.1294 9896.28609.77569909.561595.2598
9932.856558.55059950.824537.26959957.706531.3747 9986.76526.011310022.39526.4884
10042.19533.700910077.55537.519310096.39543.835410112.33552.909810308.09566.3224
10341.38 572.09510349.66572.395910359.93567.808310380.48553.748910390.75549.6035
10421.36564.309210441.67568.614510472.13 583.50110512.46584.4882 10532.6599.6774
10632.98642.007810723.06687.992410743.06695.153310793.07720.101110826.85739.5232
#Mann= 3 , 0 , 0
 9766.45   0.055       0 9766.45   0.055       010826.85   0.055       0
#XS Ineff= 2 , 0
       0                               0
Bank Sta=9766.45,10826.85
Exp/Cntr=0.3,0.1

Type RM Length L Ch R = 1 ,32424.65,499.759100,499.759100,499.759100
XS GIS Cut Line= 6
648140.151513846759795.003275429648037.015939099759823.205138957
647757.686529695759919.283471966647626.455801827759951.527313035
647432.728592684759978.184120437 647236.44648724 759986.18963652
#Sta/Elev= 30
9764.789609.18229811.109 606.9799832.027600.99699842.501601.87759852.976598.8176
9927.083554.1315 9958.96530.66329980.211524.8634 9995.44523.875610033.17525.4215
10043.75530.386410075.46538.050610096.61535.256910107.18539.1726 10149.1543.7782
 10201.1536.109110221.81548.515810262.93552.049410283.41 559.98410324.21565.9427
10354.69576.640710395.11 579.52910405.21582.4817 10425.4594.8224 10445.5598.5122
10475.66611.983810495.77616.855610555.87639.473910645.99694.449210694.55720.2707
#Mann= 3 , 0 , 0
9764.789  0.0462       09764.789  0.0462       010694.55  0.0462       0
#XS Ineff= 2 , 0
       0                10117.83       0
Bank Sta=9764.789,10694.55
Exp/Cntr=0.3,0.1

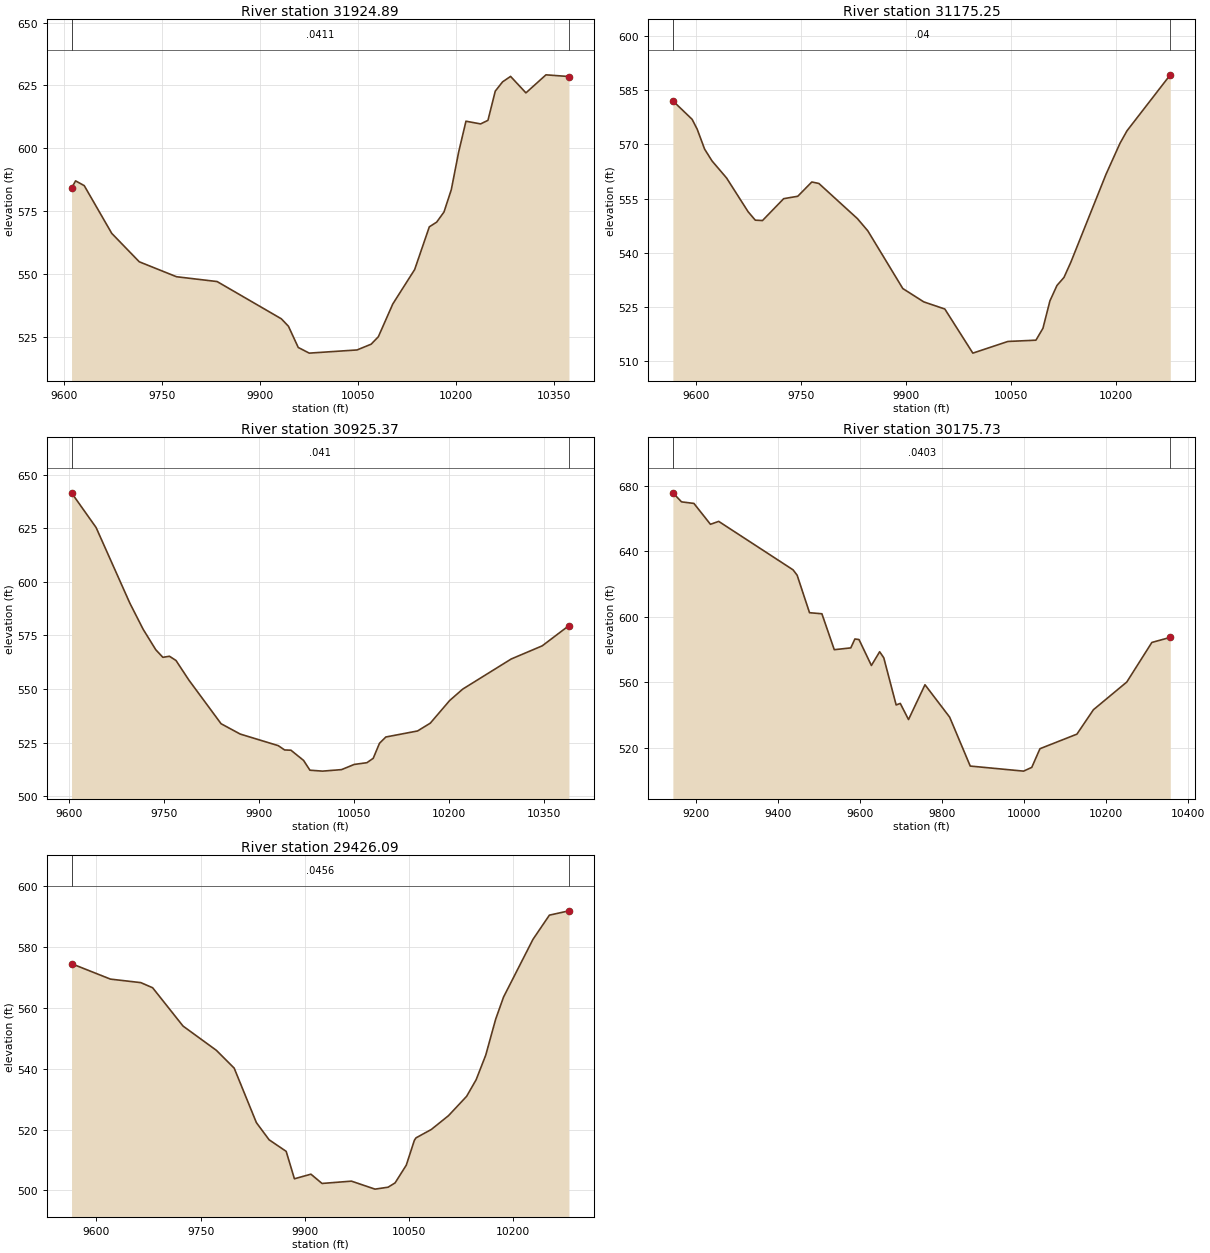
Type RM Length L Ch R = 1 ,31924.89,749.638600,749.638600,749.638600
XS GIS Cut Line= 6
648279.337833591759638.833321898648149.857964189759509.910120063
648099.041270762 759469.54733923648053.735171239759442.044537656
647910.184510241759392.669922868647633.172351407759256.958701185
#Sta/Elev= 30
 9611.55584.15629617.729 587.0779630.972585.18879673.093566.20659715.213554.8983
9772.218548.95629834.346547.04279932.616532.23219943.517529.27379958.499520.8339
9975.368 518.581 10048.5519.842810070.05522.1331 10081.1 525.08910103.22538.1295
10136.69551.819910159.12568.802710170.34570.667510181.55574.691810192.77583.5948
10203.98598.4982 10215.2 610.79710237.63609.725510248.84611.152410260.06622.7695
10271.27626.458610283.48628.614910306.96622.067410337.64629.243810372.81628.5638
#Mann= 3 , 0 , 0
 9611.55  0.0411       0 9611.55  0.0411       010372.81  0.0411       0
#XS Ineff= 2 , 0
       0                               0
Bank Sta=9611.55,10372.81
Exp/Cntr=0.3,0.1

Type RM Length L Ch R = 1 ,31175.25,249.879500,249.879500,249.879500
XS GIS Cut Line= 6
648645.619486854759717.121594442648620.632262858759650.334937738
648598.125721369759515.541767554648598.413771805759395.938120298
648618.221730544759103.775778249648614.876730069759013.282951041
#Sta/Elev= 30
9566.475582.00959593.984576.90979601.296574.15549611.844568.67579622.381565.4215
9643.309560.6725  9674.1551.34399684.364549.01339694.627548.91179724.935 554.961
9745.064555.62479765.193559.57859775.255559.16829830.485 549.4279845.281546.0594
9895.302530.11049925.355526.41629955.408524.44619995.478512.248210045.59515.4733
 10085.7 515.82710095.73519.119910105.76526.716510115.78 530.95410125.81533.1785
10135.84537.486710185.98561.728610205.98570.301310215.98573.742910277.86589.2101
#Mann= 3 , 0 , 0
9566.475    0.04       09566.475    0.04       010277.86    0.04       0
#XS Ineff= 2 , 0
       0                               0
Bank Sta=9566.475,10277.86
Exp/Cntr=0.3,0.1

Type RM Length L Ch R = 1 ,30925.37,749.638700,749.638700,749.638700
XS GIS Cut Line= 6
648931.682186147759680.251956477648893.289626251759586.045175218
648862.749448118759452.707169121648847.599463183759108.466689289
648820.032227641759026.819020669648752.013125655758933.386426442
#Sta/Elev= 30
9603.349641.52089642.179 625.3379695.606 590.0039716.611577.84059736.486568.3382
 9747.72564.7887 9758.09565.28629768.459563.31919788.918554.13929839.747533.8089
9869.921528.99429930.146523.58449940.149521.57599950.153521.4535 9970.16516.6949
9980.162512.132510000.16511.700210030.17512.403110050.17514.820210070.18515.6296
10080.18517.657110090.18524.705610100.19 527.62210150.31530.432810170.49534.0917
10201.08544.639310221.73549.969910298.46564.025710347.32570.132410389.62579.5825
#Mann= 3 , 0 , 0
9603.349   0.041       09603.349   0.041       010389.62   0.041       0
#XS Ineff= 2 , 0
       0                               0
Bank Sta=9603.349,10389.62
Exp/Cntr=0.3,0.1

Type RM Length L Ch R = 1 ,30175.73,749.638600,749.638600,749.638600
XS GIS Cut Line= 6
649985.875639958758718.995621536649722.268830079758752.122292408
 649280.18597045758799.427169559649196.837175312758803.686746108
649005.252428243758805.697508389648780.581864638758844.505905207
#Sta/Elev= 30
9142.683675.70039163.753670.18349194.027669.22559234.329656.4729 9254.48658.2428
9435.812628.65099445.876625.3497 9476.07602.43539506.265601.78159536.459579.8272
9576.718580.92359586.782586.37879596.847 586.0139627.041570.17489647.171578.5713
9657.235574.88829687.429546.04219697.494546.98949717.592537.13229757.766558.4012
9818.028538.57959868.199508.70089998.292 505.608 10018.3507.8964 10038.3519.3114
10128.41528.209910168.78543.144710250.14 560.071 10311.3584.255310356.27587.3593
#Mann= 3 , 0 , 0
9142.683  0.0403       09142.683  0.0403       010356.27  0.0403       0
#XS Ineff= 2 , 0
       0                               0
Bank Sta=9142.683,10356.27
Exp/Cntr=0.3,0.1

Type RM Length L Ch R = 1 ,29426.09,249.879600,249.879600,249.879600
XS GIS Cut Line= 6
 648951.33123827758088.686719492648843.544335127758189.233957708
648767.405216038758280.088290676648623.005470276758513.959598824
648568.090540439758572.869769678648490.702268451758625.964240029
#Sta/Elev= 30
9564.083574.53749620.128569.46049663.877568.3059 9680.86 566.6179724.576554.0333
9772.561 546.0539798.246540.19769830.213522.27629848.556516.63319873.112512.8319
9884.979503.81369908.711505.33469924.727502.28189967.058503.0394   10001500.4166
10019.84501.047310029.89502.4612   10046508.290410057.66516.468710059.98517.2652
10082.15520.043110106.86524.582410132.92530.941110146.62536.396210160.38544.4517
10174.77556.336210186.09563.589710228.41582.533310252.05590.490610280.21591.9131
#Mann= 3 , 0 , 0
9564.083  0.0456       09564.083  0.0456       010280.21  0.0456       0
#XS Ineff= 2 , 0
       0                               0
Bank Sta=9564.083,10280.21
Exp/Cntr=0.3,0.1