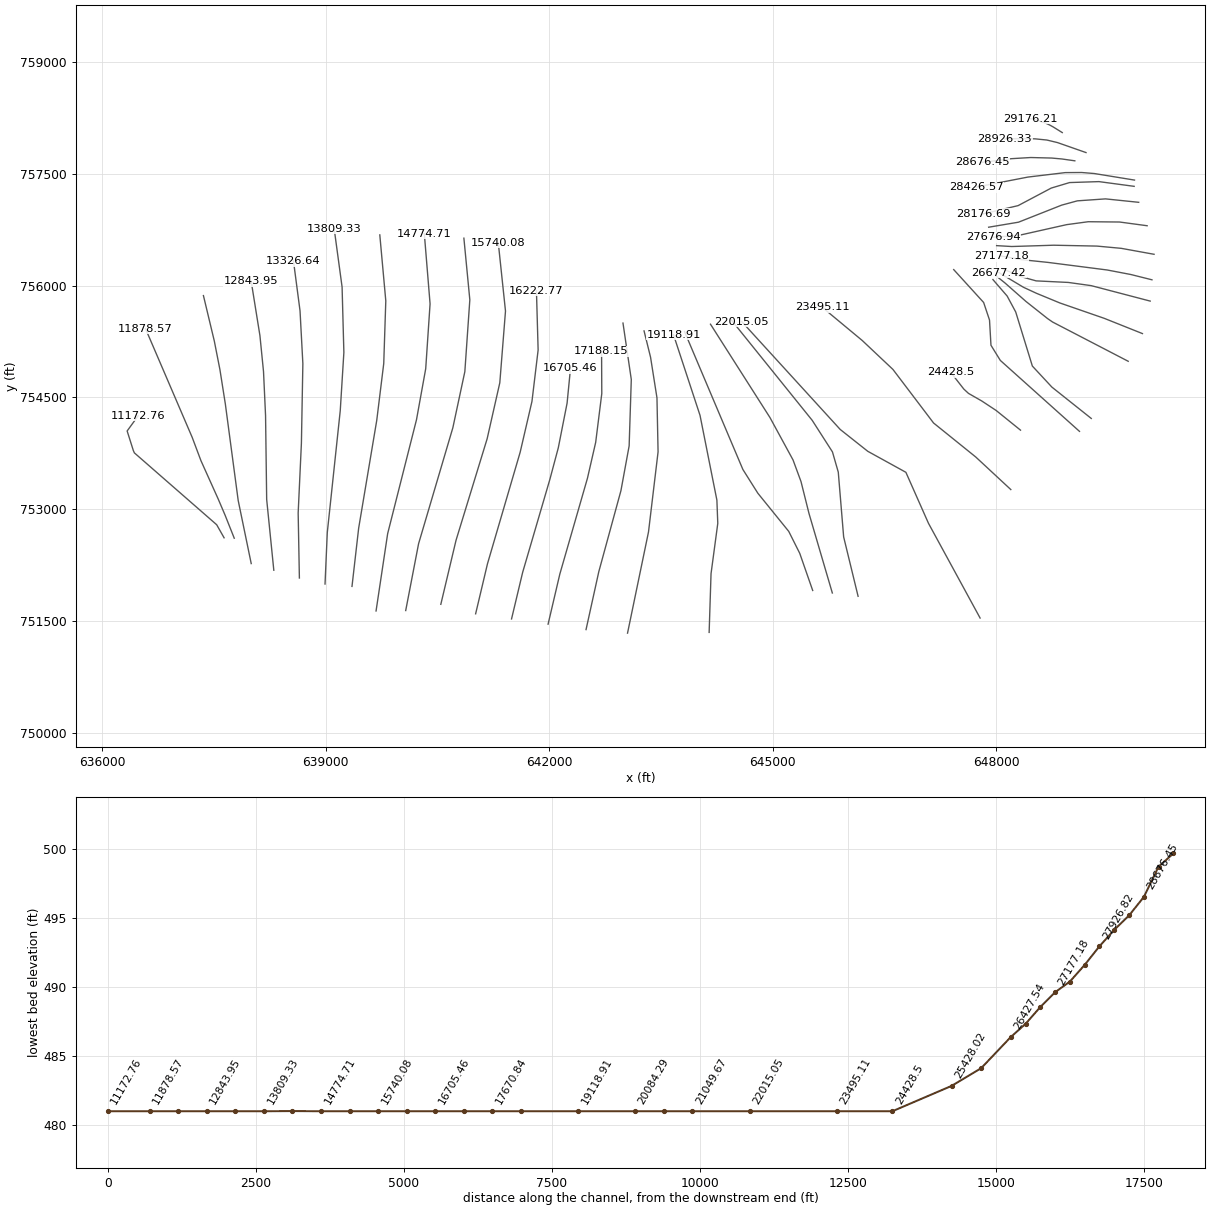
HEC-RAS study 3382_ras.prj: 3382

--- 3382_ras.g01 (geometry) --- (continued)

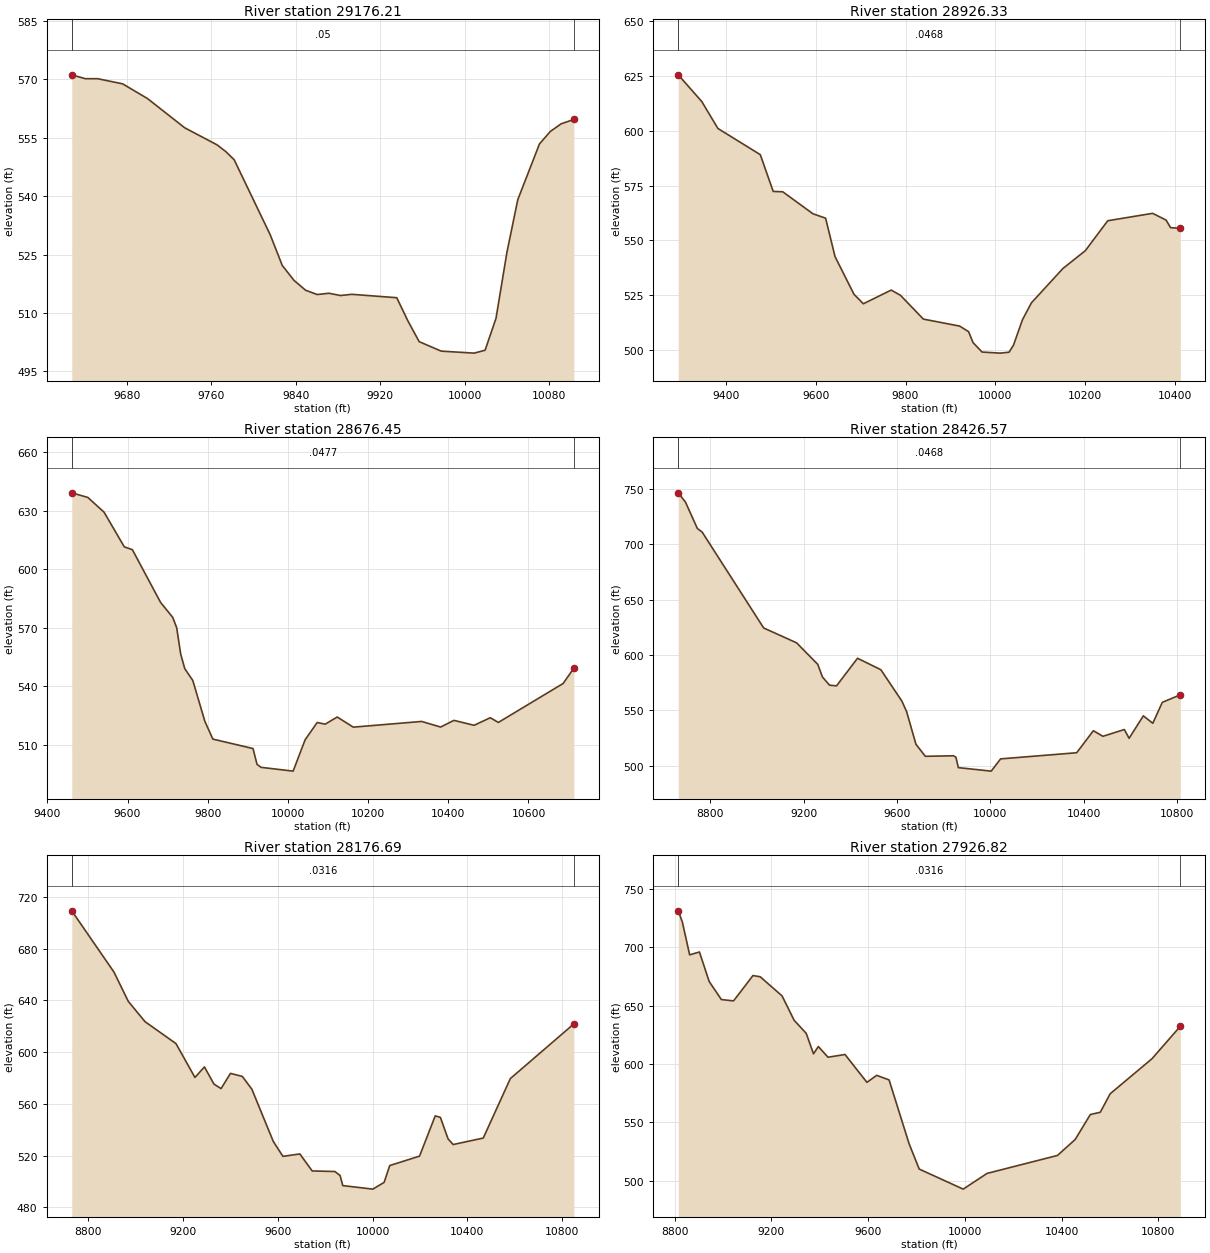
Type RM Length L Ch R = 1 ,29176.21,249.879500,249.879500,249.879500
XS GIS Cut Line= 6
648885.912522438758052.454815312648761.910882035758129.367939569
648712.676881952 758156.11064149648663.977307506758178.624240676
648554.463643844758215.470613051648453.290496455758240.296985334
#Sta/Elev= 30
9627.802571.17159640.643570.17599652.411570.17329675.946568.85579699.481565.0803
9734.783557.55699765.433 553.174 9773.72551.43679781.585549.35229815.725530.0654
9827.105522.20739838.206518.36749849.223 515.831 9860.24514.72619871.257515.0571
9882.273514.47479892.952514.78429935.514513.91129946.155507.91089956.747502.6196
9977.594500.1919 10008.8499.675310019.14500.418710029.48508.600510039.83525.5635
 10050.1539.094710070.63553.4068 10080.9556.616610091.17558.588110103.19559.7032
#Mann= 3 , 0 , 0
9627.802    0.05       09627.802    0.05       010103.19    0.05       0
#XS Ineff= 2 , 0
       0                               0
Bank Sta=9627.802,10103.19
Exp/Cntr=0.3,0.1

Type RM Length L Ch R = 1 ,28926.33,249.879500,249.879500,249.879500
XS GIS Cut Line= 6
649204.577300698757784.144680306648821.599231184757918.245222166
648679.730248362757952.360905543648523.288626879757968.116846845
648345.585414886757972.196409985648113.325047393757967.094711345
#Sta/Elev= 30
9293.323 625.4249345.734613.28389381.775601.00719476.253589.07419505.047572.3356
9526.318572.17859593.732562.15769621.824560.17049642.888542.66139685.016525.5497
9705.956521.19299768.015527.42869788.701525.0584 9839.74514.2183  9920.5511.0407
9940.602508.50169950.636503.48539970.674499.218610010.73 498.72510030.74499.1462
10040.74502.389710060.75513.958110080.75 521.63810150.77537.242610200.78545.3501
10250.78558.9925 10350.8 562.36210380.84559.295510390.85555.836910412.55555.5554
#Mann= 3 , 0 , 0
9293.323  0.0468       09293.323  0.0468       010412.55  0.0468       0
#XS Ineff= 2 , 0
       0                10123.28       0
Bank Sta=9293.323,10412.55
Exp/Cntr=0.3,0.1

Type RM Length L Ch R = 1 ,28676.45,249.879600,249.879600,249.879600
XS GIS Cut Line= 6
 649054.63865009757673.510336146648881.107465267757698.202199295
648744.117011309757710.607453018648463.038519442 757717.69888927
648202.889224589757702.106432378647808.447740358757652.197962288
#Sta/Elev= 30
9460.844639.05459501.003636.69249541.422629.13329591.861611.39189612.037609.9226
9682.435582.90889712.558575.30529722.599 569.929 9732.64556.39969742.681549.0212
9762.762 542.9379792.827 522.0219812.848512.91549912.953508.08969922.961 499.989
9932.962 498.45710012.97 496.51810042.97512.581610072.98521.4016   10093520.5826
10123.02524.224410163.05519.044410333.59 521.96210380.95519.094110414.07 522.509
 10464.4 519.99510504.77523.859810524.95521.461410686.42541.397110713.22 549.236
#Mann= 3 , 0 , 0
9460.844  0.0477       09460.844  0.0477       010713.22  0.0477       0
#XS Ineff= 2 , 0
       0                10086.49       0
Bank Sta=9460.844,10713.22
Exp/Cntr=0.3,0.1

Type RM Length L Ch R = 1 ,28426.57,249.879500,249.879500,249.879500
XS GIS Cut Line= 6
 649855.48640123757414.931792796649315.678095371757502.886193484
649146.904043853757516.575757429648925.489749312757515.215460807
648425.554709285757455.405099988647728.636017263757320.345981315
#Sta/Elev= 30
8662.745746.43768693.802738.05848744.737714.23938765.111711.04039028.867624.4332
9170.189610.9828 9260.76591.55139280.832580.16519310.907572.79959340.981572.1362
9431.092597.08449531.133586.72399621.247558.34859641.325549.00329681.481519.4014
9721.753508.56539842.839509.0198 9852.93507.6756 9863.02 498.33210003.98495.1766
10044.22506.226710370.24511.772910441.84531.6728 10482.7526.612510574.49532.7414
10594.89524.841310655.92545.080410696.52538.393710737.13557.287110814.33564.0714
#Mann= 3 , 0 , 0
8662.745  0.0468       08662.745  0.0468       010814.33  0.0468       0
#XS Ineff= 2 , 0
       09697.329         10092.8       0
Bank Sta=8662.745,10814.33
Exp/Cntr=0.3,0.1

Type RM Length L Ch R = 1 ,28176.69,249.879600,249.879600,249.879600
XS GIS Cut Line= 6
 649850.78133418757331.024763657 649377.62371187757394.446810552
648984.294079854757381.602617134648738.432698706757307.909691012
648293.336321886757072.243161583647821.219284939756960.506924005
#Sta/Elev= 30
8729.737709.22498907.926661.90418968.561639.21989039.112623.58479169.849606.5976
9250.015580.44829290.056588.58989330.092575.36719360.092571.81739400.109583.5831
9450.149581.22779490.217571.39559580.865530.99799621.485519.47299693.052521.3205
 9745.15 508.1829841.158507.74599863.004504.61949874.284496.866210001.52494.1308
10048.97499.360110072.69512.347510198.48519.628810264.76550.741610286.57549.5822
10319.04532.983710340.55528.593910467.68533.607810582.05579.5769 10850.2621.8241
#Mann= 3 , 0 , 0
8729.737  0.0316       08729.737  0.0316       0 10850.2  0.0316       0
#XS Ineff= 2 , 0
       09690.529        10209.62       0
Bank Sta=8729.737,10850.2
Exp/Cntr=0.3,0.1

Type RM Length L Ch R = 1 ,27926.82,249.879500,249.879500,249.879500
XS GIS Cut Line= 6
649911.700167891757116.608028887649466.675285514757162.665158924
649088.385475765757136.368409506648877.688288378757078.721880935
648298.724025187756849.892638893647898.173277577756782.550816032
#Sta/Elev= 30
8814.695731.13138831.592721.66818861.946693.4523 8902.37695.90328942.681670.6534
8993.068655.20089043.456654.03779123.759675.73459153.857674.68139244.039658.3176
9294.057637.44979344.057626.23139374.057608.75269394.068614.97639434.101605.8376
9504.332608.16739595.069584.33599635.602590.31829686.667586.40669769.327531.8294
9811.297510.10789993.238492.941610091.65506.386610382.99521.765110456.49535.4944
10518.92556.797610560.06558.727210601.07574.5873 10773.7604.511110890.99632.3126
#Mann= 3 , 0 , 0
8814.695  0.0316       08814.695  0.0316       010890.99  0.0316       0
#XS Ineff= 2 , 0
       0                               0
Bank Sta=8814.695,10890.99
Exp/Cntr=0.3,0.1

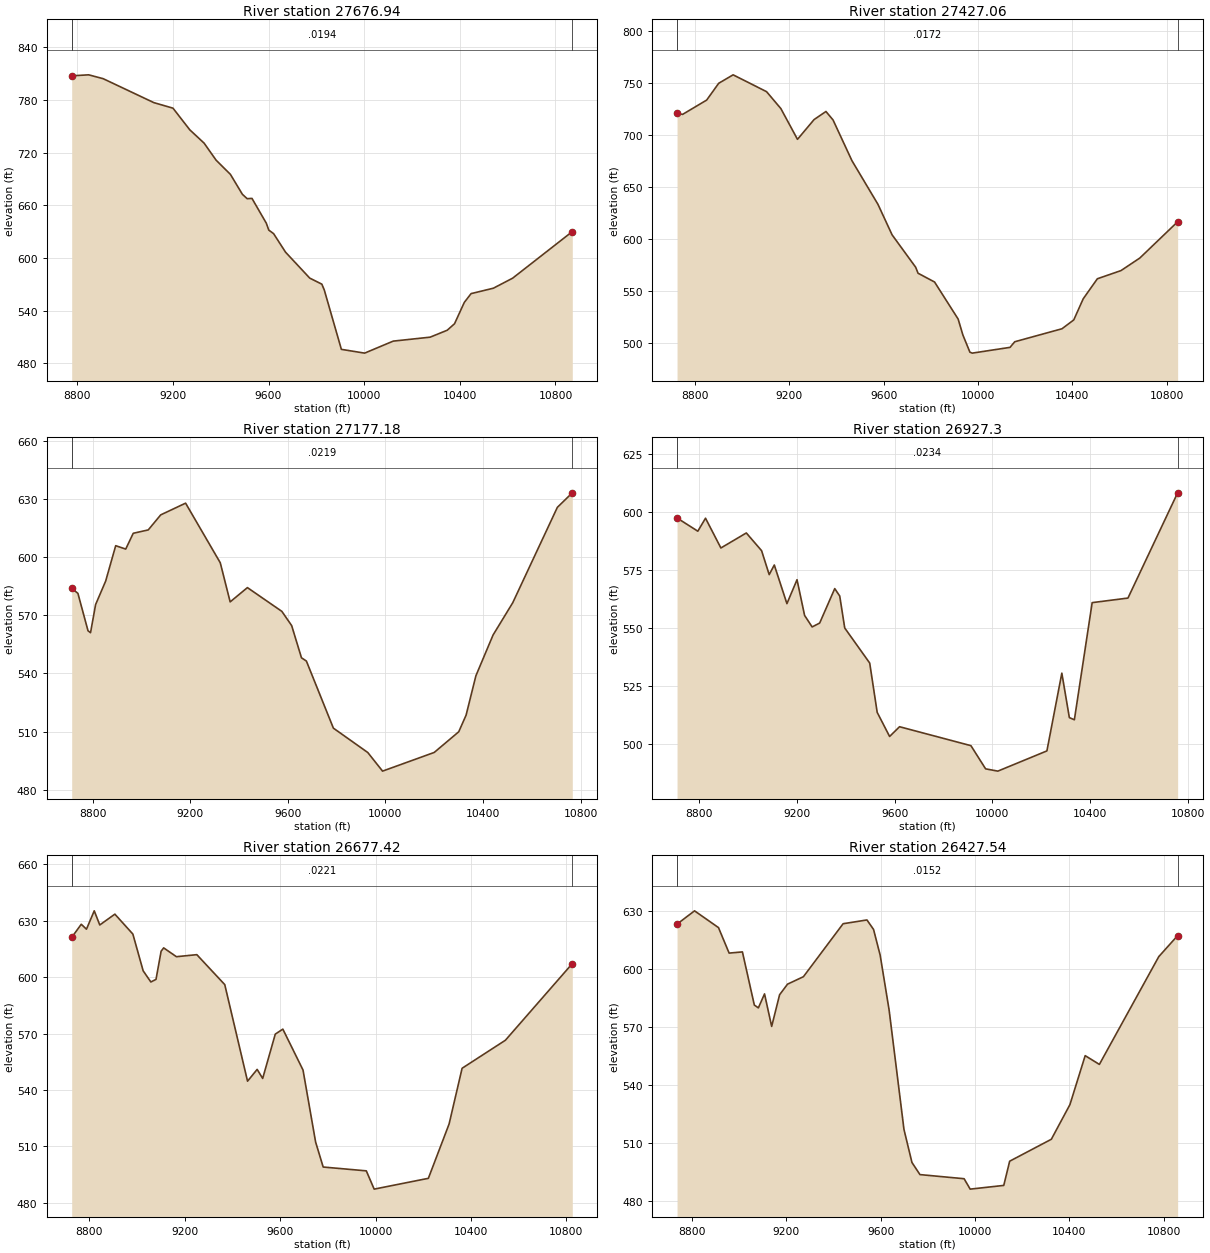
Type RM Length L Ch R = 1 ,27676.94,249.879600,249.879600,249.879600
XS GIS Cut Line= 6
650024.979210695756802.258685118649655.012119139756852.226438029
649234.952450441756856.177009522648945.196164138756817.015756714
648293.028853458756670.747372412647956.084460552756648.631205404
#Sta/Elev= 30
8777.066807.43658848.017808.5828 8908.85804.16789120.406776.93749200.635770.5947
9270.771745.98019330.814730.75959380.818   711.49440.818695.17829490.869672.4896
 9510.89667.47819530.912 667.8129591.032639.5038 9601.07631.72869621.147627.7391
9671.443606.52429772.366577.0602 9823.11570.12749833.274563.50349904.738495.8862
10001.93491.588310121.59505.2658 10275.8509.760810347.32517.659510377.97525.0813
10418.71549.3446 10447.1559.362310540.37 565.53410620.94576.972510870.31630.0073
#Mann= 3 , 0 , 0
8777.066  0.0194       08777.066  0.0194       010870.31  0.0194       0
#XS Ineff= 2 , 0
       0                               0
Bank Sta=8777.066,10870.31
Exp/Cntr=0.3,0.1

Type RM Length L Ch R = 1 ,27427.06,249.879500,249.879500,249.879500
XS GIS Cut Line= 6
650117.936625381756419.114597511649677.009476711756499.065361891
649350.748943023756529.228291363648771.223457902756540.933765321
648207.685117459756523.422210238648005.107264498756535.265971282
#Sta/Elev= 30
  8724.3721.11928747.874719.82158849.965733.58298900.962749.71858962.067757.8496
9103.847741.66549164.502725.41189234.961695.84289305.381714.85799355.679722.6119
9385.755714.47739465.955675.29739576.092633.42079636.132604.05989736.164572.8957
9746.165 567.1699816.171558.72619916.179 523.1089936.181507.84749966.184491.2398
9976.185490.378910136.21495.923310156.22  501.3210356.39513.795210406.44522.3073
10446.48542.611110506.52561.858310606.53569.691610686.57581.796910846.82 616.612
#Mann= 3 , 0 , 0
  8724.3  0.0172       0  8724.3  0.0172       010846.82  0.0172       0
#XS Ineff= 2 , 0
       0                               0
Bank Sta=8724.3,10846.82
Exp/Cntr=0.3,0.1

Type RM Length L Ch R = 1 ,27177.18,249.879600,249.879600,249.879600
XS GIS Cut Line= 6
650089.626691281756076.821757986649806.500947711756147.738876783
649488.933982059756208.482332713648696.635025799756309.927089335
648342.775705698756347.010999171648065.055086949756396.636631864
#Sta/Elev= 30
8714.046583.85578739.544581.23188780.959561.95058791.313560.9572 8812.02575.4535
8853.329587.57938894.439605.81488935.549604.07118966.382612.21199027.913613.9502
9078.989621.6971 9180.96627.73939323.148597.00459363.627576.84559434.402584.2063
9575.536571.96139615.778564.62979656.021548.01789676.142 546.3479786.807511.7638
9927.792499.20319988.412489.604110200.18499.233810300.69509.885810330.84518.4502
10371.05538.760410441.47559.785110522.16576.427110704.97625.579110766.21633.0664
#Mann= 3 , 0 , 0
8714.046  0.0219       08714.046  0.0219       010766.21  0.0219       0
#XS Ineff= 2 , 0
       0                               0
Bank Sta=8714.046,10766.21
Exp/Cntr=0.3,0.1

Type RM Length L Ch R = 1 , 26927.3,249.879500,249.879500,249.879500
XS GIS Cut Line= 6
650065.993590854 755791.07608921649274.663741871755998.384533674
648966.878280767756041.370723273648534.827728987756062.327011671
648332.601851357756119.570770591  648081.3457244756226.521169569
#Sta/Elev= 30
 8710.58597.48998795.535591.80348827.002597.3874 8889.84584.57788993.804591.0383
9056.183 583.4259087.372573.11079108.164577.25169159.792560.62139201.067570.9139
9232.023555.55779262.876550.58749293.682552.26759355.276567.08939375.694563.8844
9396.113550.14059498.204535.05139528.831513.8207 9579.59503.44589620.195507.6427
9912.027499.48979972.047489.510810022.06488.531210222.66497.235510283.67530.7037
10314.41511.565510334.96510.642310407.67561.053210553.98563.0196 10757.1608.3172
#Mann= 3 , 0 , 0
 8710.58  0.0234       0 8710.58  0.0234       0 10757.1  0.0234       0
#XS Ineff= 2 , 0
       09594.389                       0
Bank Sta=8710.58,10757.1
Exp/Cntr=0.3,0.1

Type RM Length L Ch R = 1 ,26677.42,249.879500,249.879500,249.879500
XS GIS Cut Line= 6
649961.872827617755355.058188197 649449.23948707755559.742784198
648854.377072754755765.790398029648539.463630421755895.781339802
648365.951300307755975.993717115648036.089209967756173.721902737
#Sta/Elev= 30
8726.435621.20438766.558628.20318788.321625.57588820.966635.35168844.147627.8354
8907.398633.58218982.829622.98949025.933603.45489058.261597.49669079.812598.8812
9101.245613.85579111.938615.63959165.403610.94519250.945612.03239368.032596.0978
9463.513544.72069503.781551.00149526.923546.18699579.765 569.757 9611.47572.4242
9696.017550.67169748.859512.33859780.564499.06249961.273497.03059994.226  487.31
10221.43 493.05210308.29521.939810362.87551.602210544.39566.516810824.71607.2701
#Mann= 3 , 0 , 0
8726.435  0.0221       08726.435  0.0221       010824.71  0.0221       0
#XS Ineff= 2 , 0
       0                               0
Bank Sta=8726.435,10824.71
Exp/Cntr=0.3,0.1

Type RM Length L Ch R = 1 ,26427.54,499.759100,499.759100,499.759100
XS GIS Cut Line= 6
649770.803931895754983.382815755648756.295206216755510.043155308
648690.772639007755555.005285436648399.021731953755786.095957269
648115.930629624756035.430284526647998.237631847756129.561728269
#Sta/Elev= 30
8735.949623.4215 8810.17 630.3078911.682621.63248956.798608.44119013.193609.0567
9063.741581.55229080.868580.11219106.981587.33369137.191570.5135 9170.86586.8902
9204.529592.37129271.867596.23219440.213623.6312 9541.22625.58599569.283620.6865
9597.335607.36859635.369578.94819698.343517.19949732.089500.14699766.065493.8675
9953.362491.73099979.019486.350610121.48488.269310146.53500.790510323.25512.1445
 10402.1530.079110466.77555.394210526.95550.867810778.84606.607710858.85617.4822
#Mann= 3 , 0 , 0
8735.949  0.0152       08735.949  0.0152       010858.85  0.0152       0
#XS Ineff= 2 , 0
       0                               0
Bank Sta=8735.949,10858.85
Exp/Cntr=0.3,0.1

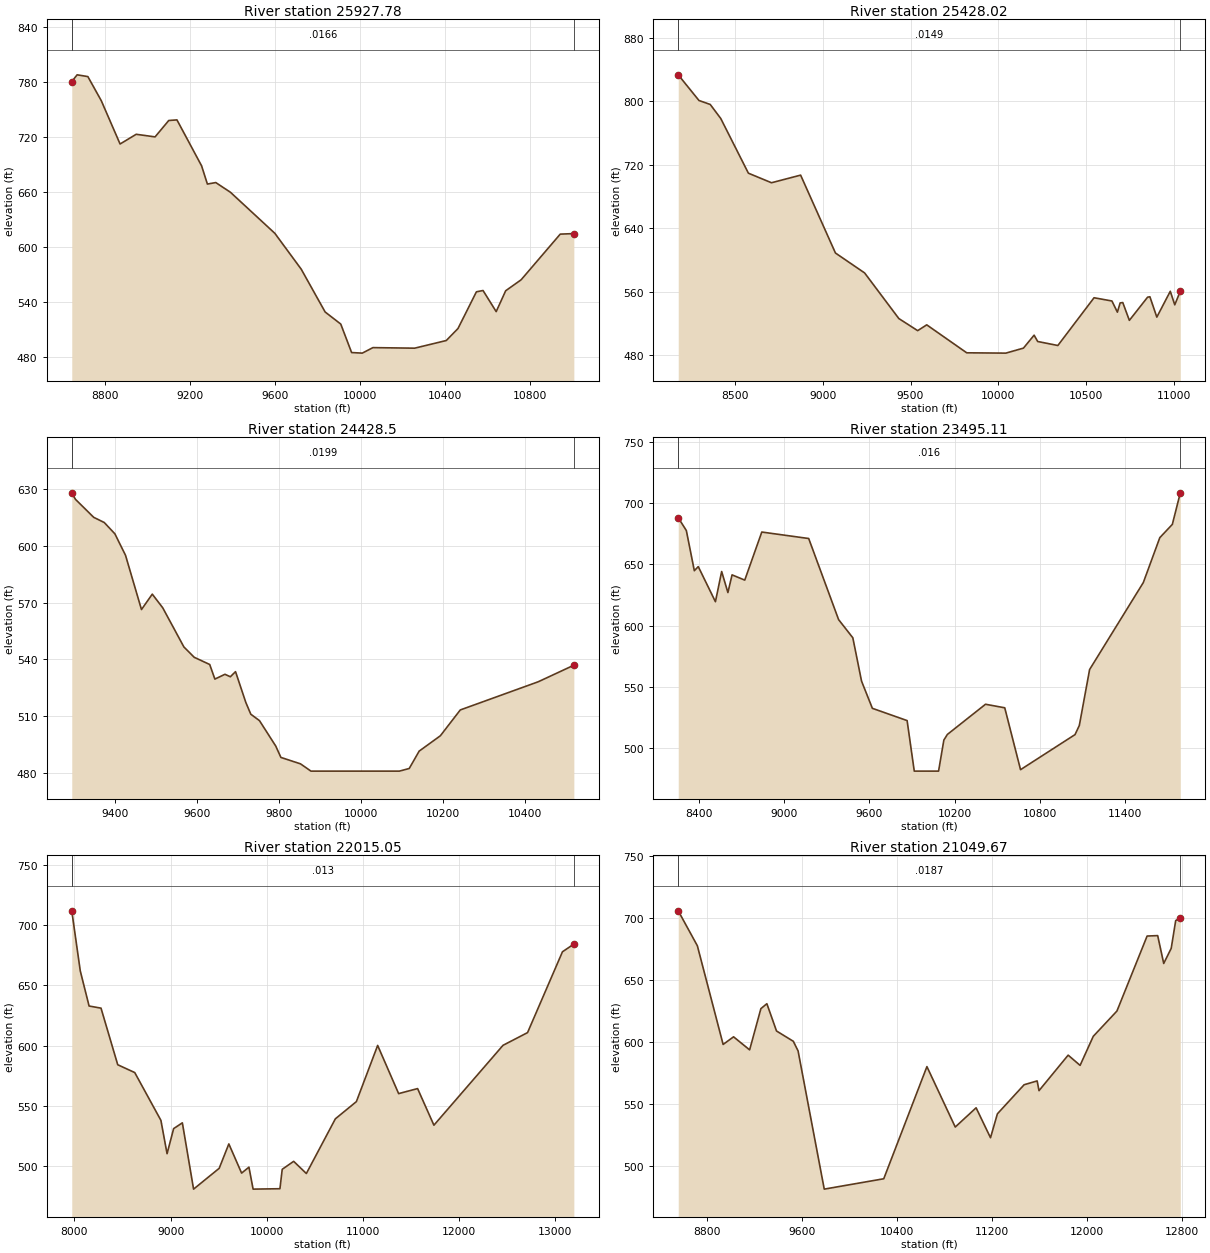
Type RM Length L Ch R = 1 ,25927.78,499.759100,499.759100,499.759100
XS GIS Cut Line= 6
649275.159721792754216.169558443648747.072085096754636.620060497
648484.699903906754919.176793155648261.324421701755645.089693345
 648146.45072924755858.733412389647955.506324265756079.708536096
#Sta/Elev= 30
8641.774780.27788667.064787.60978717.531785.70018780.724759.38288869.194712.1631
8945.026722.76289033.961719.92439098.307737.80119136.914738.44639252.917688.3396
9280.156668.47859319.721670.11349388.798659.50079597.965614.68369721.927575.5969
9834.416528.9581 9907.98515.76629958.995  484.7210009.21484.093310059.37490.0941
 10255.8489.493510404.63 497.83310459.68510.897710546.48550.973410577.59552.3843
10639.56529.374310684.22552.110510756.89564.067710941.09613.875311005.08614.4617
#Mann= 3 , 0 , 0
8641.774  0.0166       08641.774  0.0166       011005.08  0.0166       0
#XS Ineff= 2 , 0
       0                10572.17       0
Bank Sta=8641.774,11005.08
Exp/Cntr=0.3,0.1

Type RM Length L Ch R = 1 ,25428.02,999.518200,999.518200,999.518200
XS GIS Cut Line= 6
649117.096607925754042.810014199648054.878292625754994.837027055
647929.210922762755198.450431822647909.819320026755536.410841524
647830.717540354755772.670071884647429.254891657756213.690117099
#Sta/Elev= 30
8175.905833.31198294.151800.98538358.347795.99098418.275778.30968575.776709.4262
8707.522697.38418873.434706.98659071.931608.89969238.124583.8197 9433.07526.3818
 9540.67511.10829592.212518.42319820.009483.2119 10043.1482.808610143.36489.1102
10204.17 505.40610224.62497.459510339.58492.413610545.78  552.5410647.68548.4743
10678.88534.396710694.48546.010110709.47546.516210747.07 524.06710850.97553.2555
10864.12553.802610903.58528.171910980.32560.7016 11005.8543.648811037.43 560.819
#Mann= 3 , 0 , 0
8175.905  0.0149       08175.905  0.0149       011037.43  0.0149       0
#XS Ineff= 2 , 0
       0                 10252.3       0
Bank Sta=8175.905,11037.43
Exp/Cntr=0.3,0.1

Type RM Length L Ch R = 1 , 24428.5,933.390700,933.390700,933.390700
XS GIS Cut Line= 6
648325.664819402754059.160585701647997.715715617754324.004980743
647806.110960335754450.430498213647627.208644658754552.773768499
647564.661002427754610.770988956647390.365143806 754833.43646501
#Sta/Elev= 30
9293.332628.09849302.281624.67279346.809615.16239372.746 612.3869398.683606.3988
9424.619595.04749463.524566.38939489.909574.53259515.398567.33429567.108546.6205
9592.319541.14999630.136537.34529642.741529.62599667.309532.16399680.557530.8522
9693.163533.57339718.265517.29979730.468511.06229751.581507.67529791.485494.1848
9803.923 488.2169851.764 484.824 9877.37480.970210093.24480.970210117.26482.3615
10141.52491.542510193.28499.6591 10241.9513.310310432.19528.205910519.19536.9617
#Mann= 3 , 0 , 0
9293.332  0.0199       09293.332  0.0199       010519.19  0.0199       0
#XS Ineff= 2 , 0
       0                               0
Bank Sta=9293.332,10519.19
Exp/Cntr=0.3,0.1

Type RM Length L Ch R = 1 ,23495.11,1480.058300,1480.058300,1480.058300
XS GIS Cut Line= 6
 648195.54178857753261.878681122647725.245427512753698.648303762
647158.705629605 754155.37891434646614.084842857754873.510675504
646201.542659385755262.505885922 645662.23905991755710.192606285
#Sta/Elev= 30
8251.206688.23198308.456677.71138364.745644.87498392.535648.22268513.537619.5205
 8557.51644.21438601.484627.0221 8630.91641.47768720.428637.18968840.539676.4974
9171.409671.20489382.324 604.8759482.679590.01879544.134554.57819620.471532.3339
9865.492522.30499916.041480.992410087.43480.970210124.67506.3539 10149.5510.9649
10418.63535.6612 10554.2532.7597 10665.6482.157511050.08510.854711080.21518.3201
11152.77564.063311531.68635.214811647.84671.911111736.28682.761411792.47708.5719
#Mann= 3 , 0 , 0
8251.206   0.016       08251.206   0.016       011792.47   0.016       0
#XS Ineff= 2 , 0
       0                10422.49       0
Bank Sta=8251.206,11792.47
Exp/Cntr=0.3,0.1

Type RM Length L Ch R = 1 ,22015.05,965.379700,965.379700,965.379700
XS GIS Cut Line= 6
647783.345882767751537.902553661647090.491294126752809.484171195
646787.613888349753493.402282357646276.154385321753775.315678874
645906.263689294754068.431181117  644585.2036946755515.629152468
#Sta/Elev= 30
7972.692711.98128061.022 662.1478152.678632.97178276.669631.19878450.558584.2048
8627.312577.73668899.323538.03538963.269510.35779031.575531.20059122.245536.0048
9238.831480.97029505.064498.24919605.418518.50089738.064  494.27 9814.32499.2028
9857.623480.970210136.42481.304910160.22497.415410279.15504.0439 10411.1493.9204
10712.55539.319310931.13553.617611152.23600.243911370.25560.250311567.29564.4321
11737.02534.032312455.41600.351512710.35610.887713073.13  677.9813191.45684.3751
#Mann= 3 , 0 , 0
7972.692   0.013       07972.692   0.013       013191.45   0.013       0
#XS Ineff= 2 , 0
       0 9731.13        11151.26       0
Bank Sta=7972.692,13191.45
Exp/Cntr=0.3,0.1

Type RM Length L Ch R = 1 ,21049.67,482.689800,482.689800,482.689800
XS GIS Cut Line= 6
646146.108575036751829.916706746 645952.39256987 752626.12186682
645880.264769112753495.730015017645802.053993183753767.308098389
645530.624007918754190.553419918644430.469770477755555.771106701
#Sta/Elev= 30
8555.644  705.548716.833677.36388934.256597.72359022.258603.86669157.751593.3441
9252.696  626.619303.189630.58899384.476608.57429525.998600.27499566.257592.5355
9787.036480.9702 10288.8489.324510652.87579.827410891.74531.073311067.64546.5923
11189.11522.437511247.13541.727911472.62565.203811582.41568.2917 11598.1560.4266
11843.95589.085111944.68580.833912055.82604.289212255.27624.669712509.85 685.196
12598.95685.540412649.87663.066412713.03 675.267 12750.9697.669312789.74699.8978
#Mann= 3 , 0 , 0
8555.644  0.0187       08555.644  0.0187       012789.74  0.0187       0
#XS Ineff= 2 , 0
       0                10644.88       0
Bank Sta=8555.644,12789.74
Exp/Cntr=0.3,0.1

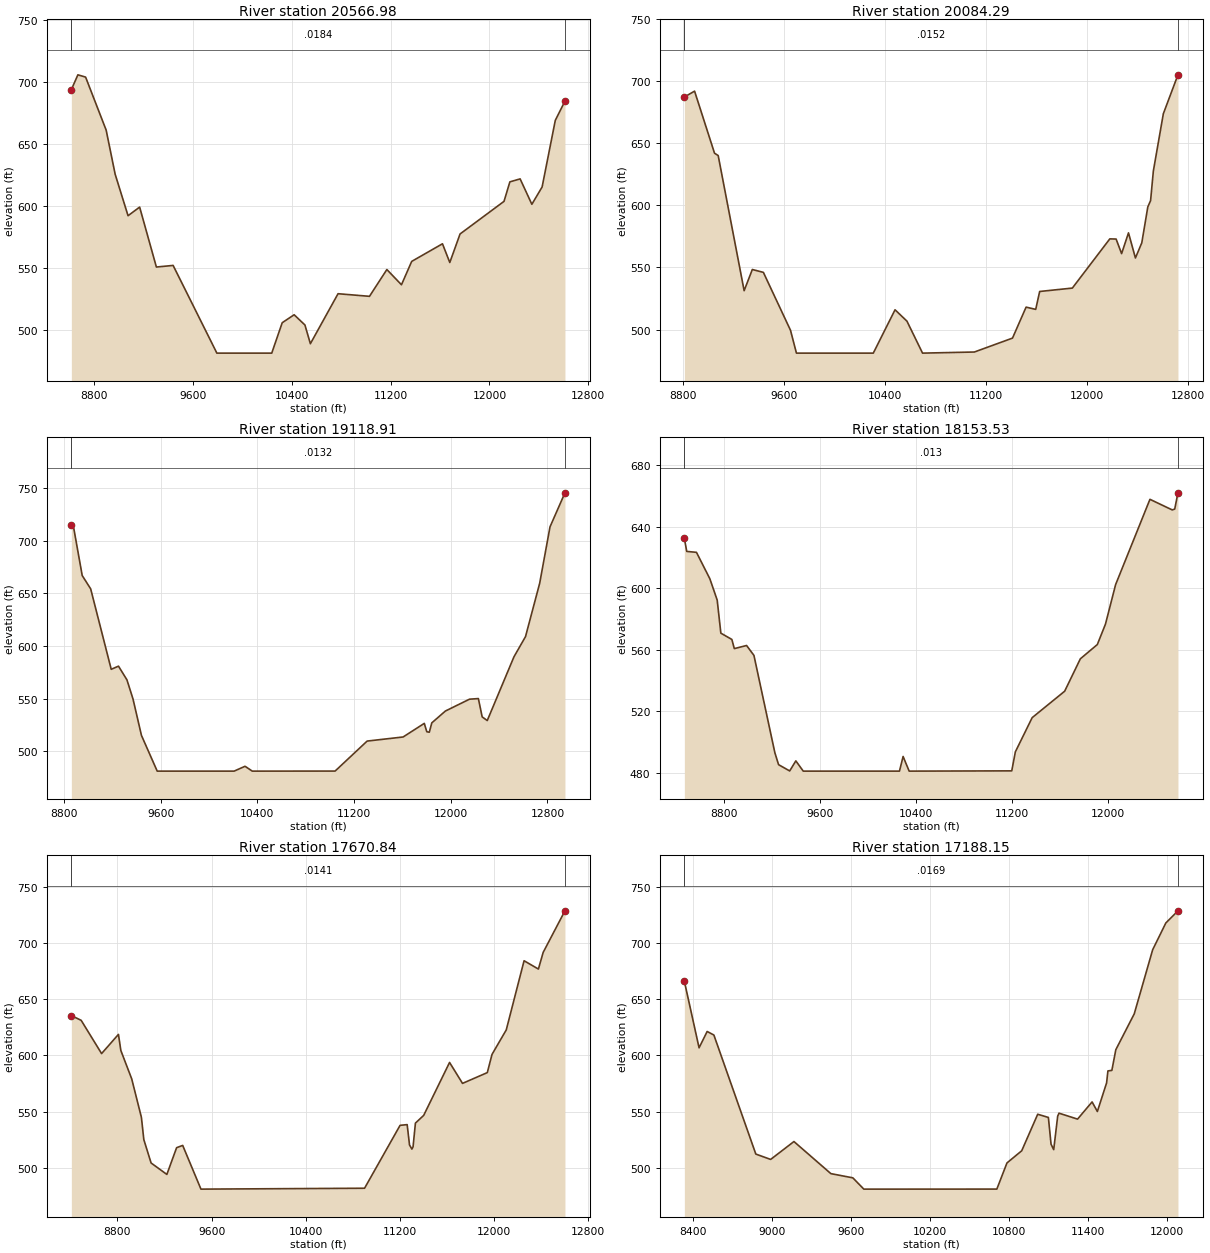
Type RM Length L Ch R = 1 ,20566.98,482.689800,482.689800,482.689800
XS GIS Cut Line= 6
645800.375045598751874.108210501645487.361362043752940.602588096
645380.156794029753368.912534105645273.156709979753659.233146317
644963.977968903754227.452864628644165.501392524755480.780056342
#Sta/Elev= 30
8615.061693.80328668.026705.80038730.471703.97028896.989 661.1278969.841625.4724
 9074.11591.9724 9167.97598.94259303.547550.52759439.123551.82289793.266480.9702
 10237.5480.970210322.25505.528910418.96511.971210506.22503.693910550.39488.5757
10774.31528.965711028.82526.859111169.56548.502111287.77536.188711370.55555.0705
11619.69569.302611679.01554.175811762.06577.222112117.98 603.58612165.43619.3272
12248.48621.731512343.39601.222512426.44   615.212533.21669.033112611.25684.5533
#Mann= 3 , 0 , 0
8615.061  0.0184       08615.061  0.0184       012611.25  0.0184       0
#XS Ineff= 2 , 0
       0                10393.58       0
Bank Sta=8615.061,12611.25
Exp/Cntr=0.3,0.1

Type RM Length L Ch R = 1 ,20084.29,965.379600,965.379600,965.379600
XS GIS Cut Line= 6
645536.986642939751907.774397301645363.163505396752406.056690387
 645215.57353409752700.664492645644801.159388971753212.377856349
644600.216520003 753531.17427756643816.900652841755382.119469646
#Sta/Elev= 30
8813.747687.41888894.599 692.1479052.355 642.1349081.458640.20879286.727531.3125
9351.466548.38639438.858546.06779653.446499.40869700.455480.970210308.44480.9702
10480.49515.908610574.69506.741710698.07480.970211108.15481.866911409.79493.0842
11517.23518.040811593.32516.236511624.66530.657611883.17 533.40212179.55 573.065
12229.24572.918212272.83561.176312327.31577.916612382.17557.670912432.52569.8946
12480.12598.806112502.06603.900312524.01627.7771   12603673.939512718.61705.2969
#Mann= 3 , 0 , 0
8813.747  0.0152       08813.747  0.0152       012718.61  0.0152       0
#XS Ineff= 2 , 0
       0                10728.35       0
Bank Sta=8813.747,12718.61
Exp/Cntr=0.3,0.1

Type RM Length L Ch R = 1 ,19118.91,965.379600,965.379600,965.379600
XS GIS Cut Line= 6
644147.251092385751345.090597388644172.759990696752133.044786238
644263.230173437752807.689712588644251.254347306753120.182874426
644024.903313271754257.891626022 643668.89546016755340.231207569
#Sta/Elev= 30
8860.981714.98598880.891711.99928950.891666.95669020.891654.29789190.918577.7844
9250.931580.79329320.976567.7653 9371.03549.62219441.106514.92739571.376480.9702
10207.74480.970210298.11485.578910358.18480.970211043.19481.022211308.33 509.544
11605.81513.437411781.18526.367911801.82518.440611822.55517.963811843.29526.8494
11955.63538.1046 12155.3549.382812228.61549.947712260.09532.539512302.14529.0584
12523.42589.767812618.59608.8629 12735.9659.635512821.27713.240212944.87745.6051
#Mann= 3 , 0 , 0
8860.981  0.0132       08860.981  0.0132       012944.87  0.0132       0
#XS Ineff= 2 , 0
       09674.288        11161.99       0
Bank Sta=8860.981,12944.87
Exp/Cntr=0.3,0.1

Type RM Length L Ch R = 1 ,18153.53,482.689800,482.689800,482.689800
XS GIS Cut Line= 6
643052.184354238751335.313215804643333.488829607752692.487433611
643462.039038579753767.608775249643447.100781327 754492.84338123
643361.137767732755037.804340075643273.866454219755390.945945071
#Sta/Elev= 30
 8472.66632.39838492.565623.90198573.597623.29868685.264606.07188746.235592.2367
8776.721570.71878868.382  566.638888.793560.67568990.844562.69449052.269556.2676
9226.649492.90789257.483485.17539349.984481.08869401.374487.64099463.041480.9702
10264.45480.970210294.76490.504410345.26480.970211199.79481.140711229.79493.5069
11369.82 515.75511640.48532.954511771.32554.047811912.68563.329811980.63576.6541
12064.76602.273612350.91657.790612536.57650.8896 12557.3 651.45212584.19662.0143
#Mann= 3 , 0 , 0
 8472.66   0.013       0 8472.66   0.013       012584.19   0.013       0
#XS Ineff= 2 , 0
       09301.528        10944.76       0
Bank Sta=8472.66,12584.19
Exp/Cntr=0.3,0.1

Type RM Length L Ch R = 1 ,17670.84,482.689800,482.689800,482.689800
XS GIS Cut Line= 6
642495.403536646751382.895024392642666.753811675752160.635614843
642963.532279559753246.810313354643073.763387507753847.864387844
643102.647680323754738.971509663642991.183484485755495.942476686
#Sta/Elev= 30
8408.233635.44088491.691631.25728665.135601.64938808.308618.72418828.822604.3615
8921.135579.10549003.345544.8893 9023.94525.04789085.724504.23719219.652494.0626
9302.373517.86049354.074519.88669509.176480.970210898.94481.763411200.68537.7614
11260.83538.392411280.86520.269811300.88516.609711310.89518.617711330.92539.7296
11400.98546.584111621.01593.741311731.09575.104111941.59584.707411981.73600.9455
12102.53 622.69912253.93684.297912375.64676.899212416.21691.745912601.09728.7355
#Mann= 3 , 0 , 0
8408.233  0.0141       08408.233  0.0141       012601.09  0.0141       0
#XS Ineff= 2 , 0
       09191.541         10940.5       0
Bank Sta=8408.233,12601.09
Exp/Cntr=0.3,0.1

Type RM Length L Ch R = 1 ,17188.15,482.689800,482.689800,482.689800
XS GIS Cut Line= 6
641986.090620415751455.654012425642143.669391533752127.812234265
642514.639609755753414.852274601642624.700476877 753895.07526252
642706.675548128754549.715157494642703.823809655755116.812872677
#Sta/Elev= 30
 8333.91666.13488445.747606.82128507.127621.34768558.277618.18888876.938512.1847
8989.531 507.4169166.577523.34339447.126494.77339614.093491.02029697.577480.9702
10708.15 480.99910785.16504.289810897.23 515.13711018.85547.663811099.81544.7904
11120.05521.025111140.28516.131211170.51545.932311180.59548.605611321.48543.3123
11431.91558.623311472.01550.097711542.15575.588111552.16 586.23711582.19586.7258
11612.21605.115511752.26 637.06511892.29694.158311992.34717.995212084.34728.7949
#Mann= 3 , 0 , 0
 8333.91  0.0169       0 8333.91  0.0169       012084.34  0.0169       0
#XS Ineff= 2 , 0
       09077.471        10895.03       0
Bank Sta=8333.91,12084.34
Exp/Cntr=0.3,0.1

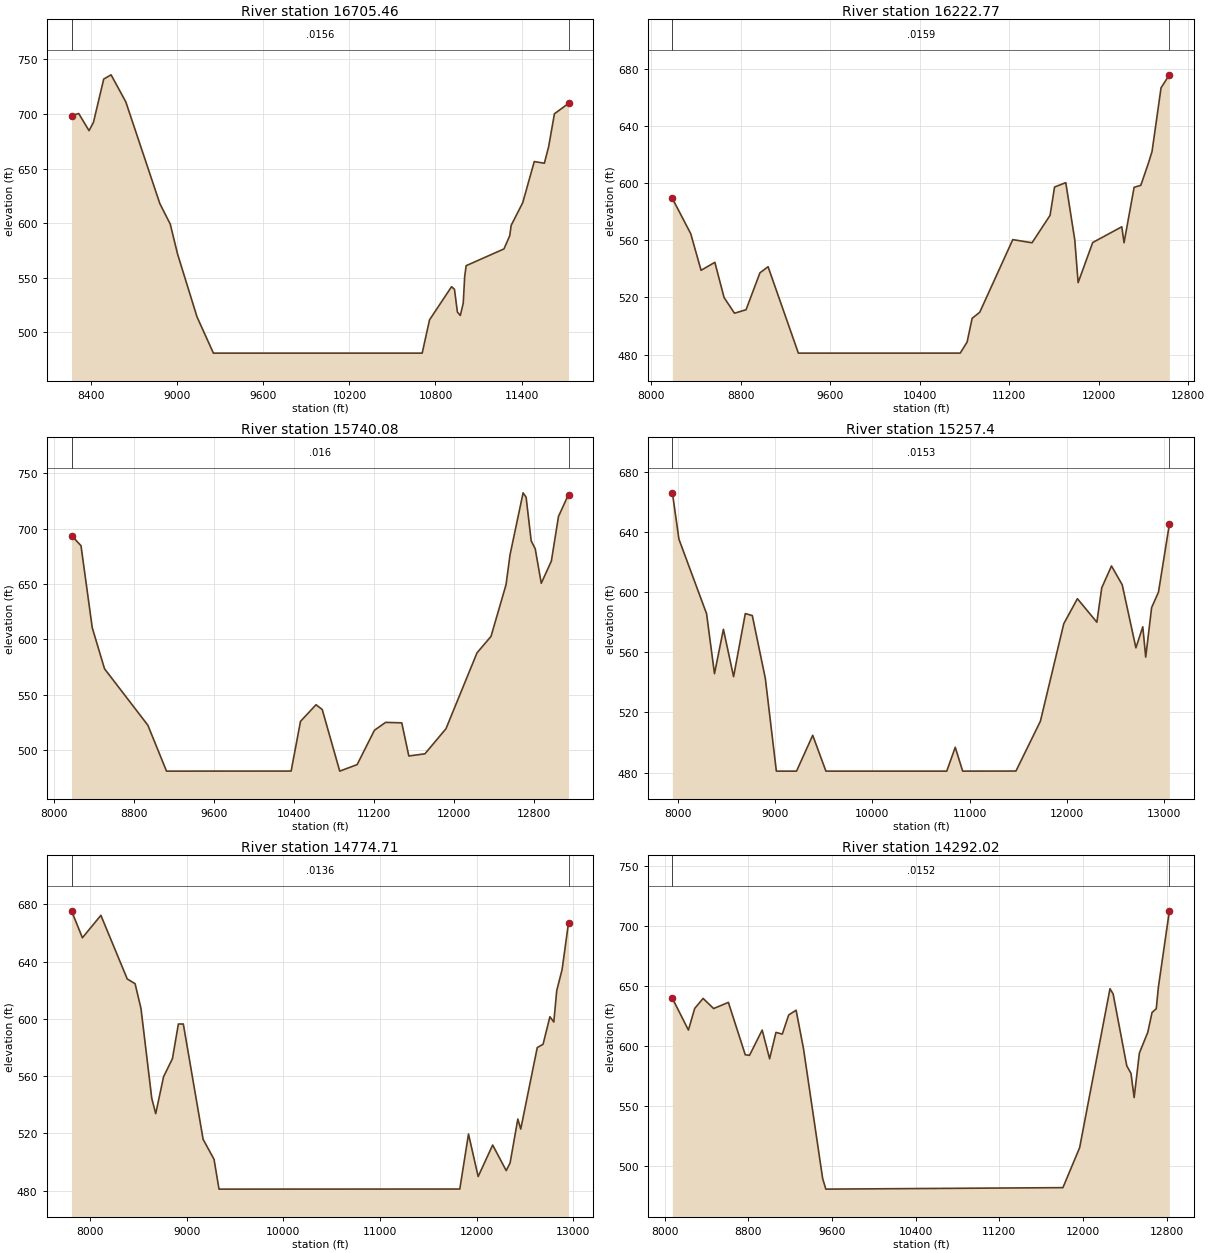
Type RM Length L Ch R = 1 ,16705.46,482.689800,482.689800,482.689800
XS GIS Cut Line= 6
641495.648479408751525.717175427  641644.9382674752151.528794712
 642010.39080204753399.952752715642123.289518371753823.158059598
642241.059475363754421.362753333642287.314191911754893.024346969
#Sta/Elev= 30
8261.529698.53748311.952700.35118383.683684.69448414.425692.20118486.156731.9134
8537.392735.79388640.199711.05948877.579617.8985 8950.05599.1463 9001.89571.3857
9136.838514.17499251.266480.9702 10707.3480.970210758.59511.428110912.11541.7921
 10932.5539.447410952.89518.645810973.28515.462710993.67526.811311003.87551.2645
11014.06561.040311277.61576.382911317.97588.480511328.06597.982911408.68618.7318
11489.15656.387911559.44654.847611589.54670.086211629.66700.116111727.88709.5906
#Mann= 3 , 0 , 0
8261.529  0.0156       08261.529  0.0156       011727.88  0.0156       0
#XS Ineff= 2 , 0
       09100.468        10852.71       0
Bank Sta=8261.529,11727.88
Exp/Cntr=0.3,0.1

Type RM Length L Ch R = 1 ,16222.77,482.689800,482.689800,482.689800
XS GIS Cut Line= 6
641013.711152576751594.565364975641172.693718159752265.735916395
641611.387525926753762.965834869 641769.56240815 754444.43429922
  641852.4522424755134.332307143641829.852006893755929.133950198
#Sta/Elev= 30
8189.992589.44648353.945564.7181 8446.21539.03438569.476544.64318651.808519.9561
8744.788508.9537  8848.1511.39118972.469537.30269045.097541.5621  9315.8480.9702
10762.22480.979510823.79488.777510868.63505.391110936.54509.628911231.79560.5628
11403.74558.352111564.91577.577511605.12597.439311705.53600.529411785.73560.3561
 11815.8530.412811945.92558.517712205.97569.574112225.98 558.39612316.08597.2513
12376.14598.649412446.24614.760112476.37622.419812556.74667.028812631.21676.1172
#Mann= 3 , 0 , 0
8189.992  0.0159       08189.992  0.0159       012631.21  0.0159       0
#XS Ineff= 2 , 0
       09113.595                       0
Bank Sta=8189.992,12631.21
Exp/Cntr=0.3,0.1

Type RM Length L Ch R = 1 ,15740.08,482.689800,482.689800,482.689800
XS GIS Cut Line= 6
640546.642416953751721.939437887640750.662497201 752580.89968737
641168.445787366 753944.25642077 641338.10775582754694.740914453
641414.502845769 755657.06134061641317.739469116756573.448399363
#Sta/Elev= 30
8174.853693.74418269.738684.60628382.067610.53918504.919573.41668937.863522.4872
9124.665480.970210370.25481.030310463.95 525.92210619.25540.946210681.31536.6266
10856.11480.970211030.11486.859311203.25517.896711314.75525.011311476.38524.5742
11546.91494.658111707.72496.599311918.19519.2804 12228.3587.788112368.38602.6847
12518.67649.4113 12558.8676.477212689.24732.3625 12719.5728.347512769.93688.9928
12810.27681.862912870.79650.685212971.79670.7106   13043711.035213143.14730.8436
#Mann= 3 , 0 , 0
8174.853   0.016       08174.853   0.016       013143.14   0.016       0
#XS Ineff= 2 , 0
       09189.527        11448.14       0
Bank Sta=8174.853,13143.14
Exp/Cntr=0.3,0.1

Type RM Length L Ch R = 1 , 15257.4,482.689900,482.689900,482.689900
XS GIS Cut Line= 6
640075.377175533751638.379745448640248.238755227752535.340173165
640708.343575395754092.310441571640869.027469346754844.714853943
640935.860000163755807.878068895640856.191074563756635.364359504
#Sta/Elev= 30
7946.272666.16298013.582635.30198297.391585.73558378.776545.8362 8470.46575.3325
8575.103543.83578695.559585.8204  8767.4584.4723 8901.03 542.7179014.507480.9702
9221.677480.9702 9388.12504.81659523.701480.970210765.01480.970210852.45496.8377
10928.87480.970211475.99481.0221 11727.1514.153711967.44579.046612107.47595.7144
12307.53580.064312357.57602.964512457.68617.497412568.04604.956512708.61563.0082
12779.18577.012312809.43 556.85412869.93589.7626 12940.5600.067213052.54645.4106
#Mann= 3 , 0 , 0
7946.272  0.0153       07946.272  0.0153       013052.54  0.0153       0
#XS Ineff= 2 , 0
       09319.657                       0
Bank Sta=7946.272,13052.54
Exp/Cntr=0.3,0.1

Type RM Length L Ch R = 1 ,14774.71,482.689800,482.689800,482.689800
XS GIS Cut Line= 6
639677.586478167751632.873590795639833.361788932752671.169035972
 640220.24580626754199.578703444640343.866683573754883.530819513
640402.412398908755753.944544675640325.258722498756695.524545712
#Sta/Elev= 30
7809.663 675.5177922.347656.68328113.612672.35868386.323627.87878467.333624.5873
8528.203607.32678639.936544.4295 8680.68533.73828762.168559.56558853.843572.2193
8915.216596.39788966.386596.38939171.192515.79289284.285501.77189335.691480.9702
11826.54481.033811916.55 519.47412016.56489.778312166.58511.789712306.74493.9453
 12346.8499.234412426.92529.951412457.05522.969212627.78579.926312688.14582.2517
12758.79601.499212799.16597.769612829.44619.769912884.52634.3412 12951.2667.0734
#Mann= 3 , 0 , 0
7809.663  0.0136       07809.663  0.0136       0 12951.2  0.0136       0
#XS Ineff= 2 , 0
       09470.834        11927.53       0
Bank Sta=7809.663,12951.2
Exp/Cntr=0.3,0.1

Type RM Length L Ch R = 1 ,14292.02,482.689800,482.689800,482.689800
XS GIS Cut Line= 6
639354.632315514751962.341684538639444.035029699752743.308431017
639686.683891205754189.712379265639780.700815985754953.641872071
639808.266463886755793.800941753639727.795895146756679.234138459
#Sta/Elev= 30
8073.844640.04168227.024 613.5288287.285631.57258367.694639.89398468.297631.4632
8609.352636.58088770.922592.93288811.322592.4654 8932.73 613.5379003.635 589.604
 9064.41611.60429125.186610.16979186.064626.09419257.138630.06639328.213597.8422
9510.976489.85479541.437480.9818 11808.8482.217411968.83515.475512259.25647.9755
12289.32643.633812419.85583.705512460.06577.432712490.21557.291512540.48594.4164
12621.08611.787212661.47628.198312701.86631.337612722.06 649.26112827.31712.8935
#Mann= 3 , 0 , 0
8073.844  0.0152       08073.844  0.0152       012827.31  0.0152       0
#XS Ineff= 2 , 0
       0                               0
Bank Sta=8073.844,12827.31
Exp/Cntr=0.3,0.1

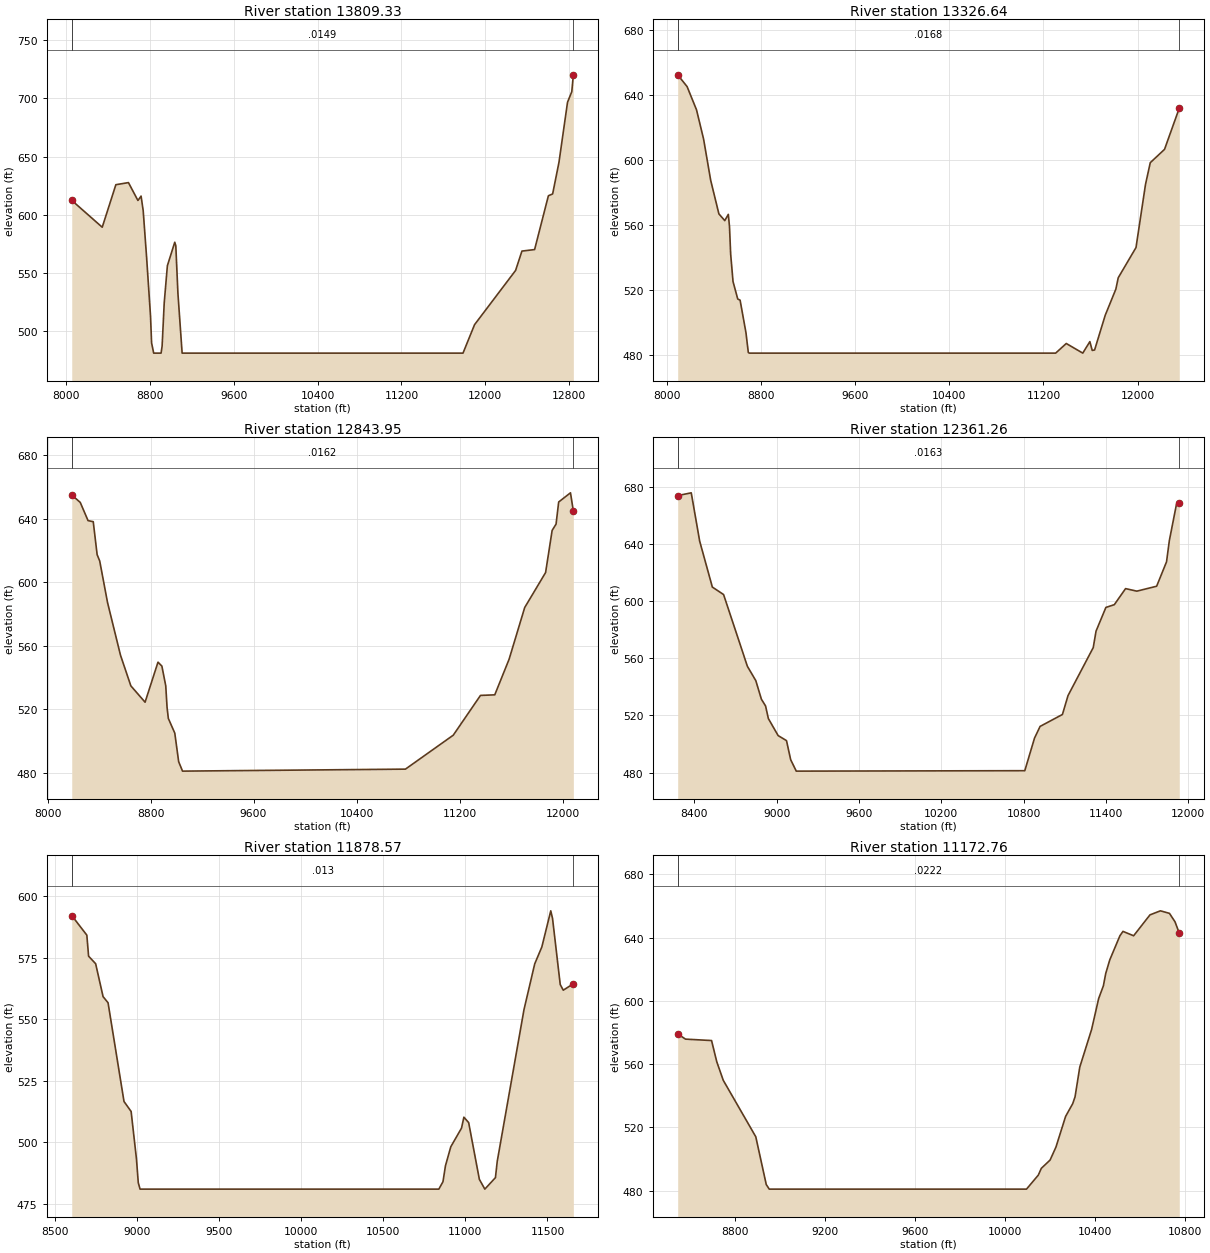
Type RM Length L Ch R = 1 ,13809.33,482.689800,482.689800,482.689800
XS GIS Cut Line= 6
638992.762729608751994.271353882639023.076167942752684.594867002
639197.013250699754320.354954267639245.636132347755101.940353126
 639221.73431459755979.581433428639115.885155885756759.547422989
#Sta/Elev= 30
8055.103 612.3538345.929589.24598476.063625.8242 8596.27627.62978686.481612.2332
8716.558616.02888736.609603.61948768.687564.16758806.856512.55338816.893489.7303
8836.967480.97028907.225480.97028917.262487.00848937.336524.20288967.453556.1248
9037.835 576.356 9047.89573.38139067.999532.50099108.217480.970211787.78480.9702
11897.94505.446112289.49552.087812349.94568.726412470.86570.040812602.38616.3204
12642.85617.880412703.57645.221812784.87696.742612825.59705.8073 12840.4720.3231
#Mann= 3 , 0 , 0
8055.103  0.0149       08055.103  0.0149       0 12840.4  0.0149       0
#XS Ineff= 2 , 0
       09077.346                       0
Bank Sta=8055.103,12840.4
Exp/Cntr=0.3,0.1

Type RM Length L Ch R = 1 ,13326.64,482.689800,482.689800,482.689800
XS GIS Cut Line= 6
 638648.73552627 752075.11579489638632.314141653752946.587555606
638675.815343188753885.329236481 638695.33434885754951.478689294
638657.373462437755660.286766798638569.503444987756328.647828211
#Sta/Elev= 30
8091.794652.56258171.817645.30018251.897 630.9788311.957612.95038371.988587.6199
8442.007566.8163 8492.02562.67648522.029566.53748532.031559.02318542.034542.0296
8562.039525.1233 8602.05514.34138622.056513.64918672.056493.56518692.056481.3135
8702.056480.970211303.64480.970211393.75486.906411534.07480.983711594.28488.0646
11614.35482.648511634.42482.893711724.81504.309411815.27 520.43911835.37527.4349
11986.44546.086112067.15585.010212107.55 598.393 12228.8606.611712354.15632.0229
#Mann= 3 , 0 , 0
8091.794  0.0168       08091.794  0.0168       012354.15  0.0168       0
#XS Ineff= 2 , 0
       08945.327                       0
Bank Sta=8091.794,12354.15
Exp/Cntr=0.3,0.1

Type RM Length L Ch R = 1 ,12843.95,482.689800,482.689800,482.689800
XS GIS Cut Line= 6
638305.455594473752179.552405206638209.656643289753129.642417214
638194.783272693754253.367201584638167.285084244754845.598218053
638119.153819028755328.184113065638001.911063263756056.805294407
#Sta/Elev= 30
8188.147655.08678254.202650.41878314.759638.93588355.078638.2683 8385.29617.4928
8405.431 613.4638465.854587.3685 8566.56554.12658647.073534.75728757.612524.4375
8857.965549.6891 8888.07547.19918918.176534.79698928.211521.33838938.246514.2138
8988.386 504.9369018.447486.93049048.508480.970210779.53482.2268 11150.9503.6294
11362.29528.711311473.31529.073711584.34551.483811705.74584.1319   11868606.1951
11918.75632.757211949.26636.751511969.62650.681712061.26656.460812083.46644.9956
#Mann= 3 , 0 , 0
8188.147  0.0162       08188.147  0.0162       012083.46  0.0162       0
#XS Ineff= 2 , 0
       08859.102        11120.82       0
Bank Sta=8188.147,12083.46
Exp/Cntr=0.3,0.1

Type RM Length L Ch R = 1 ,12361.26,482.689800,482.689800,482.689800
XS GIS Cut Line= 6
638002.312855939752268.712034198637827.493048582753115.382811824
637654.929157344754411.203205186637582.390624897754871.081049155
637507.011648162755255.128316309 637360.99217556755864.910737996
#Sta/Elev= 30
8278.672674.11518377.499676.0562 8439.08642.14248531.327609.98158613.221604.7504
8786.825554.4416 8848.09 544.4128888.806531.40098919.304526.63258939.636517.8105
9010.797505.89129071.792502.3547 9102.29488.97889142.953480.970210808.68481.2703
10879.68504.137210920.26512.323711083.03520.678611123.82533.927911307.53567.5462
11328.02579.103611399.76595.714811461.24597.663811543.22608.911611625.52607.1326
11769.73610.585611841.84 627.68911862.44 642.65411914.13667.988111934.74669.1196
#Mann= 3 , 0 , 0
8278.672  0.0163       08278.672  0.0163       011934.74  0.0163       0
#XS Ineff= 2 , 0
       09400.054        10643.11       0
Bank Sta=8278.672,11934.74
Exp/Cntr=0.3,0.1

Type RM Length L Ch R = 1 ,11878.57,705.803300,705.803300,705.803300
XS GIS Cut Line= 6
 637774.50875017 752609.21534813637651.875653207752917.644089043
637560.162723392753132.996807069637327.392539442753650.280212626
637210.112300098 753962.64990972636583.709644586755421.469816417
#Sta/Elev= 30
8602.997592.1366 8694.92584.16288705.635575.61338748.579  572.558793.773559.1869
8824.135556.69338921.277516.57388964.658512.51618997.266493.13359008.135483.5786
9019.004480.970210838.53480.970210863.71 483.97710878.85490.463310911.46498.1936
10976.68505.757910991.16510.192911020.16508.011711085.38 484.939 11118.7480.9702
11183.21485.637911194.08492.203411357.13553.915911422.35572.471711465.84579.3727
11520.19594.044811531.06590.915311577.84 564.08411596.28561.802811657.66564.4058
#Mann= 3 , 0 , 0
8602.997   0.013       08602.997   0.013       011657.66   0.013       0
#XS Ineff= 2 , 0
       09482.479        10401.28       0
Bank Sta=8602.997,11657.66
Exp/Cntr=0.3,0.1

Type RM Length L Ch R = 1 ,11172.76,233.504000,233.504000,233.504000
XS GIS Cut Line= 6
637638.252886551752614.713289988637538.819518255752789.953815889
636434.397273557753754.192105007636420.453959005753785.557989862
636337.226836996754048.043528598636484.319699781754250.296214935
#Sta/Elev= 30
8546.714579.09348581.474575.81028697.199574.90628720.344561.51078749.221549.7657
8893.659 514.0898940.221483.86768953.502480.970210096.41480.970210148.92489.8482
10162.05494.079810201.18499.358910227.19507.539810270.08526.943510301.56534.9741
10312.05539.309610333.03558.092610385.48581.861610416.95 601.47910437.93609.4871
10448.42617.333510466.25625.881510511.37641.156810525.05643.930710572.27641.1539
10644.94654.367410691.28656.926910731.49655.333610756.22 649.97410775.14642.8049
#Mann= 3 , 0 , 0
8546.714  0.0222       08546.714  0.0222       010775.14  0.0222       0
#XS Ineff= 2 , 0
       09796.679                       0
Bank Sta=8546.714,10775.14
Exp/Cntr=0.3,0.1