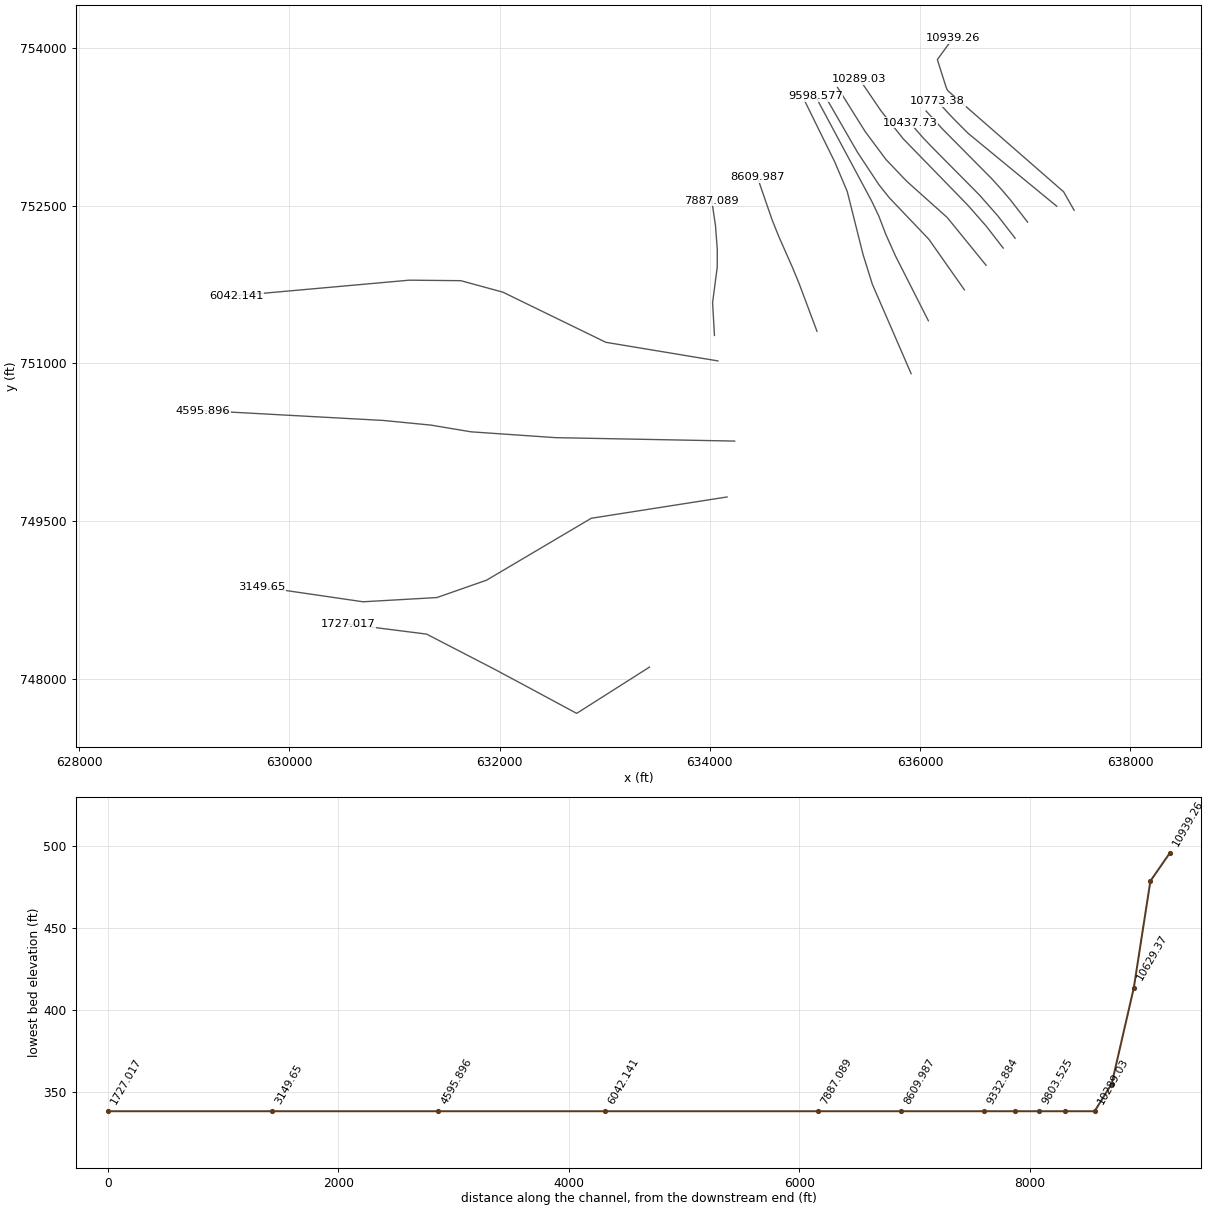
HEC-RAS study 3382_ras.prj: 3382

--- 3382_ras.g01 (geometry) --- (continued)

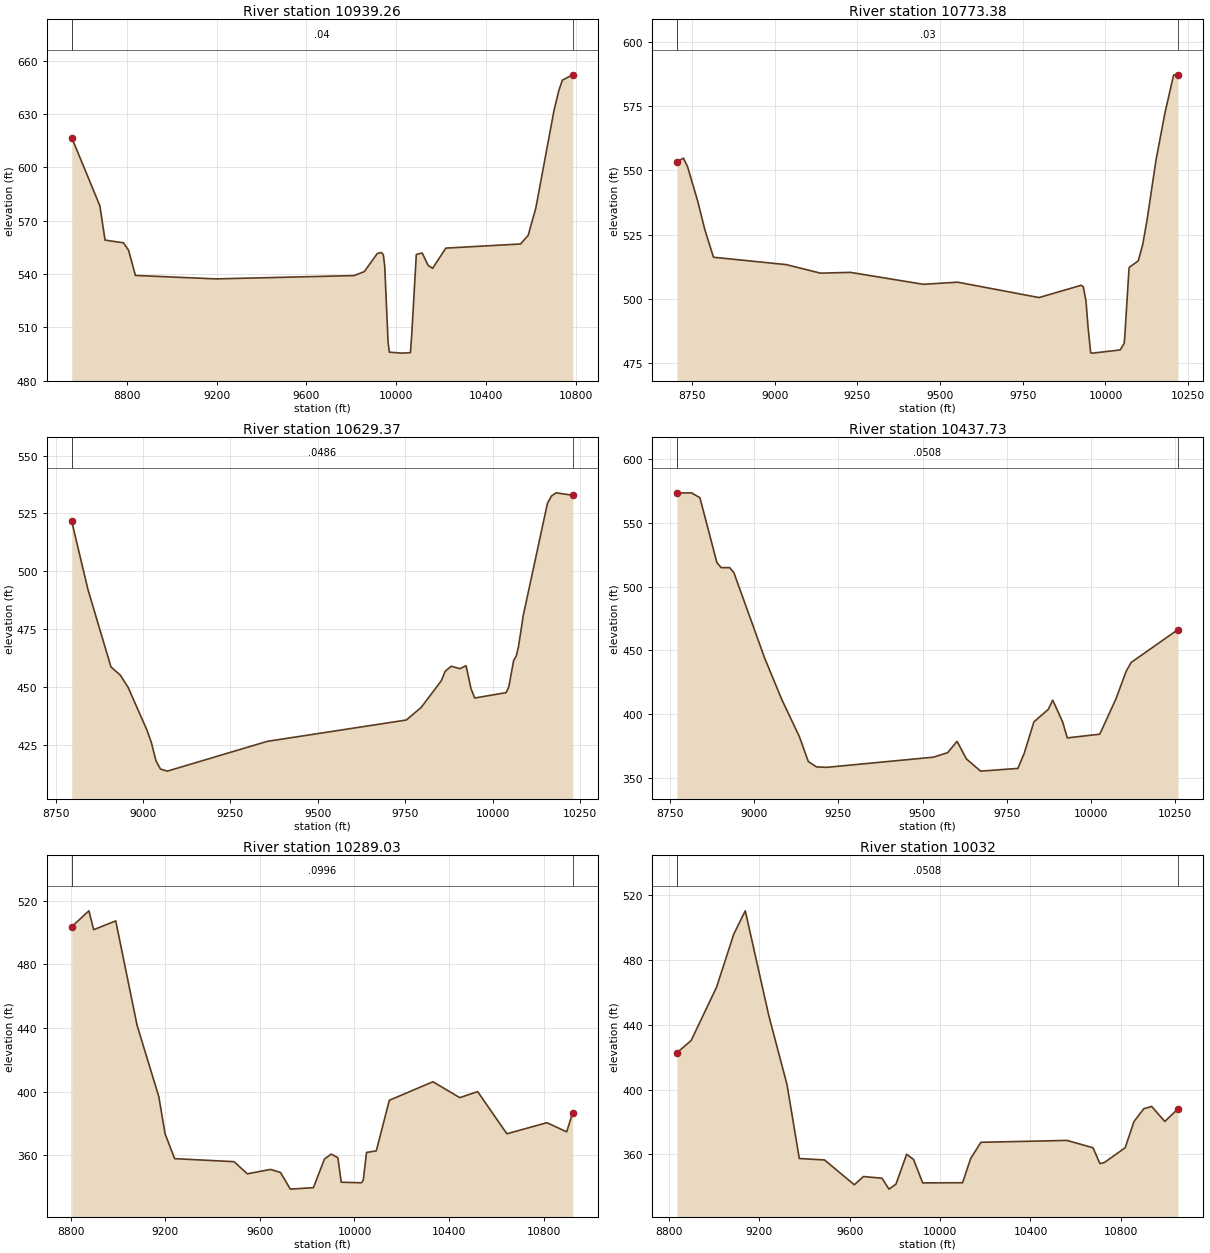
Type RM Length L Ch R = 1 ,10939.26,165.882100,165.882100,165.882100
XS GIS Cut Line= 6
637465.418772787752456.588462502637365.985404491752631.828988403
636261.563159794753596.067277521636247.619845241753627.433162376
636164.392723233753889.918701112636311.485586017754092.171387449
#Sta/Elev= 30
8555.956616.73438681.126 578.4288704.271559.10828786.333557.59358808.872553.3813
8839.455539.2485 9198.03537.30759811.849539.17179857.439541.37959915.178551.5812
9933.211552.15029941.985550.96139948.225544.5467 9963.24501.59899968.797496.1275
 10023.3495.582710062.54 495.85110068.63506.4609 10088.8 551.06810115.06551.8369
10141.32544.887710161.23543.242910220.09554.610810552.33 556.93110586.33561.7718
10620.34577.092310701.32632.016610722.35643.022110738.42649.028110784.38652.0118
#Mann= 3 , 0 , 0
8555.956    0.04       08555.956    0.04       010784.38    0.04       0
#XS Ineff= 2 , 0
       09901.946        10162.83       0
Bank Sta=8555.956,10784.38
Exp/Cntr=0.3,0.1

Type RM Length L Ch R = 1 ,10773.38,144.007100,144.007100,144.007100
XS GIS Cut Line= 6
637299.968833506 752494.89164865636455.921282649 753189.26797682
 636328.14556852753317.686110422636256.204161525753393.576484933
636183.341162294753474.902604774636166.627795591 753494.90866898
#Sta/Elev= 30
8705.083553.26388724.466554.78418736.734551.58218768.215537.80988789.212526.9042
8815.435516.14329035.245513.26749138.838509.94289229.481510.24959449.616505.5925
9553.209506.42119799.355500.42729926.955505.22919933.096504.57619941.132499.0601
9947.203489.1149 9955.31478.8955 9961.31478.7612 10044.4480.004310056.46482.5621
10058.18484.904110070.99511.419210071.96512.215610099.11 514.73810112.54 521.041
10125.97530.933310152.82554.111210179.67572.361210205.98 587.21910219.04587.2648
#Mann= 3 , 0 , 0
8705.083    0.03       08705.083    0.03       010219.04    0.03       0
#XS Ineff= 2 , 0
       09890.888        10163.52       0
Bank Sta=8705.083,10219.04
Exp/Cntr=0.3,0.1

Type RM Length L Ch R = 1 ,10629.37,191.640400,191.640400,191.640400
XS GIS Cut Line= 6
 637022.57000033752344.190529237636859.112385114752555.318723653
636780.066469588752648.167295981636683.303830454752754.962608294
636216.166401864753226.540277071636057.348484407753400.531082048
#Sta/Elev= 30
8796.261521.62268842.822492.06638908.448 458.7348935.274455.13028957.668449.8454
9011.346431.44429024.234425.93879037.122418.2196 9050.01414.60329069.653413.6979
9355.666426.55959753.078  435.779795.941 441.2689853.095452.72779864.085456.7875
9881.451459.01819906.405457.93949923.984459.19639938.161449.26879948.725445.2841
10038.52447.592810046.21450.111210059.99461.481610067.59 463.46910073.77 467.368
10087.55480.966310156.57 529.33410168.37532.5593 10181.8533.884410228.84 532.828
#Mann= 3 , 0 , 0
8796.261  0.0486       08796.261  0.0486       010228.84  0.0486       0
#XS Ineff= 2 , 0
       09881.514        10164.55       0
Bank Sta=8796.261,10228.84
Exp/Cntr=0.3,0.1

Type RM Length L Ch R = 1 ,10437.73,148.703000,148.703000,148.703000
XS GIS Cut Line= 6
636904.451335587752190.421556746636740.993720371752401.549751162
636565.185165711752601.193635803636098.047737121 753072.77130458
636026.106330094753148.661679103635904.194191065 753288.70010135
#Sta/Elev= 30
 8771.01573.45358813.866573.67338839.093569.83118889.549518.92978902.163514.9747
8927.391514.99058940.005 511.0079031.707 443.7179081.988 411.6149134.521382.2678
9160.809362.85699185.238358.59899215.024 358.2439532.541366.24259574.483369.7564
9602.445 378.6619630.407364.8242 9672.35355.28379783.172357.40679802.156369.5326
9830.511393.91269873.044403.67749886.471410.98149915.578394.14819929.755381.3753
10026.15384.2617 10074.2411.998210104.17433.467510119.15440.523510258.23466.3539
#Mann= 3 , 0 , 0
 8771.01  0.0508       0 8771.01  0.0508       010258.23  0.0508       0
#XS Ineff= 2 , 0
       09869.892        10166.88       0
Bank Sta=8771.01,10258.23
Exp/Cntr=0.3,0.1

Type RM Length L Ch R = 1 ,10289.03,257.026400,257.026400,257.026400
XS GIS Cut Line= 6
636790.799166997752096.794695904636627.341551781 752307.92289032
636451.532997121752507.566774961635839.591162263753136.360938085
635629.324980972 753400.73700125635421.486302618753705.951582412
#Sta/Elev= 30
8804.615503.76488877.273 513.788 8897.49501.91388990.798507.46729080.957441.7203
9172.889 396.7849199.307373.4097 9239.79357.76759490.822355.87179547.058348.2287
9644.925350.98429687.203349.0915 9728.81 338.5829826.444339.50539873.116357.5106
9901.471360.63599929.826358.39569944.004342.924410029.76342.5751 10037.2344.3025
10050.98361.671710092.32362.682910147.28394.501710331.68406.179110445.21396.1751
10520.78399.971910644.21373.4301 10813.7380.4035 10897.2374.651810922.52386.7446
#Mann= 3 , 0 , 0
8804.615  0.0996       08804.615  0.0996       010922.52  0.0996       0
#XS Ineff= 2 , 0
       09880.503         10188.1       0
Bank Sta=8804.615,10922.52
Exp/Cntr=0.3,0.1

Type RM Length L Ch R = 1 ,   10032,228.475400,228.475400,228.475400
XS GIS Cut Line= 6
636627.628291673751933.565223255636259.029147575 752386.76612262
  635873.3225718752731.968754297635676.529147223752938.063027112
635477.026144008753206.045721528635214.914623183 753624.97548408
#Sta/Elev= 30
8836.229422.72668899.184430.37539011.055463.10769087.462  495.97  9138.4510.3481
9242.864445.47169323.017403.11939377.395357.48539489.057356.59199620.832341.2648
9661.139346.36849743.192345.3012 9774.24 338.5829804.835341.6354 9852.36360.1317
9882.829356.88119923.373342.431610099.76342.524910135.31357.428910180.85367.4813
10561.94368.644310676.79364.113210707.28354.355810725.96354.900910818.83364.0994
10858.09380.311710901.25388.184210936.16389.607610994.35380.351611052.52388.0708
#Mann= 3 , 0 , 0
8836.229  0.0508       08836.229  0.0508       011052.52  0.0508       0
#XS Ineff= 2 , 0
       09870.865        10175.94       0
Bank Sta=8836.229,11052.52
Exp/Cntr=0.3,0.1

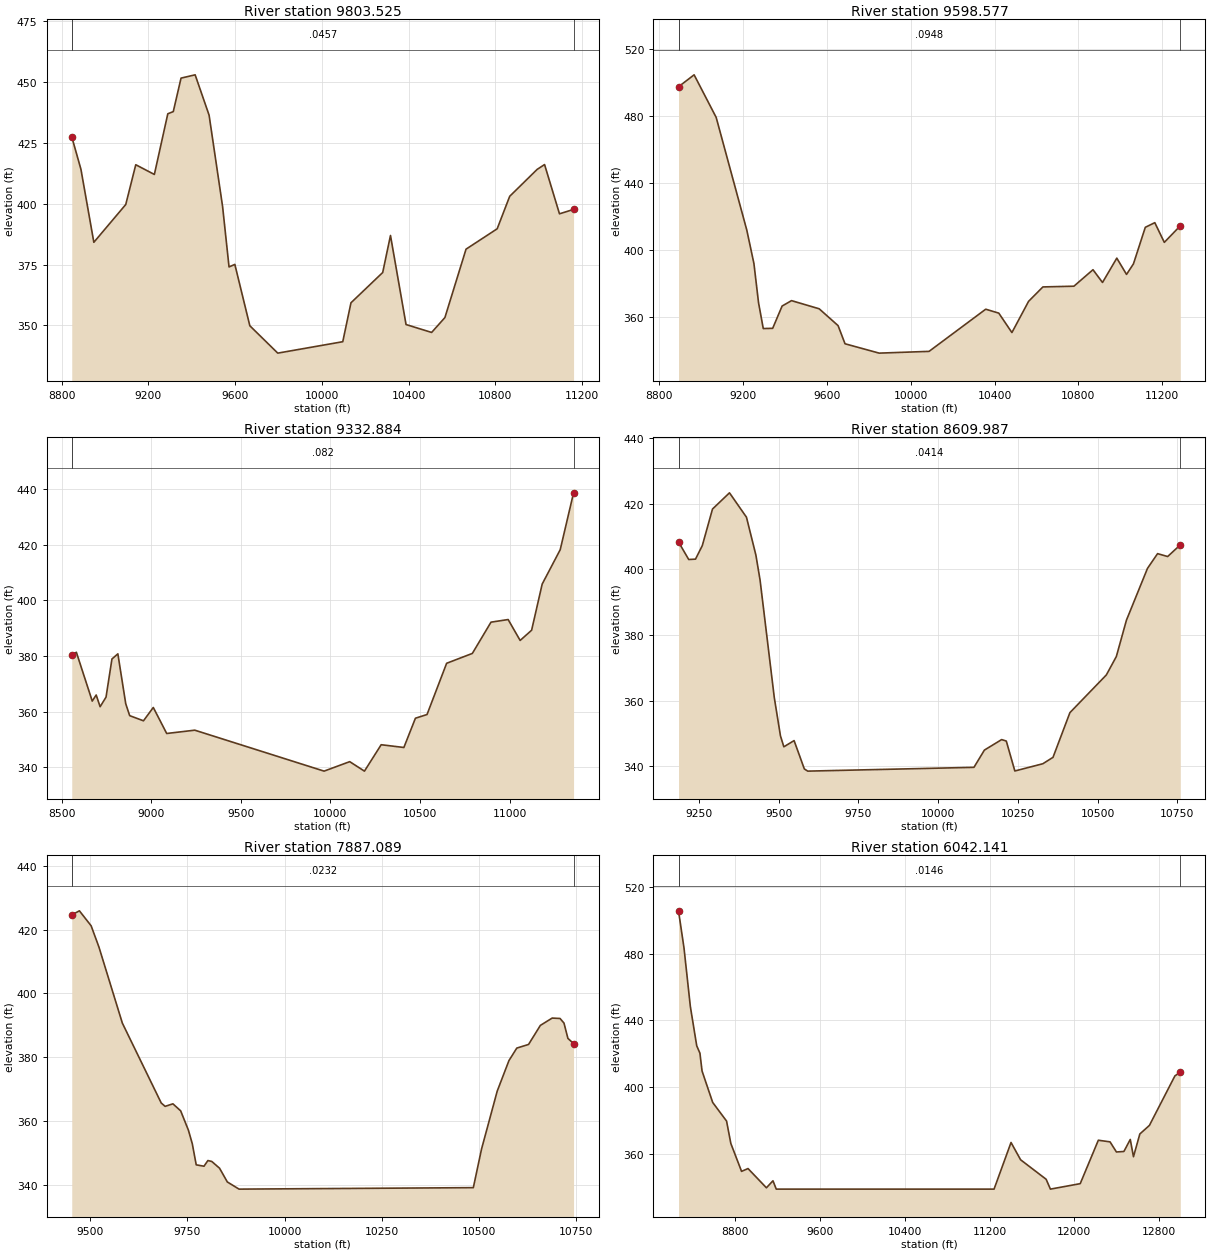
Type RM Length L Ch R = 1 ,9803.525,204.948000,204.948000,204.948000
XS GIS Cut Line= 6
636421.858260845751699.303957394636082.835607199752181.388254002
635708.926895132752573.406785578635608.812402943752698.927676789
635405.228823376753007.090894944635079.625879546753571.942296579
#Sta/Elev= 30
 8846.85427.51118889.218 414.1258948.744384.13429095.855399.66039142.039416.0124
9227.807412.01999289.772 436.9589314.984437.8507 9350.82451.61529415.833452.9671
 9480.14436.39299542.313398.90939572.116374.00189598.882 375.0469668.025349.8272
9796.842 338.58210096.52343.273610134.42 359.267 10280.7 371.71410316.59386.9293
10388.38350.331610506.35347.083410567.65353.206810664.96381.307610808.62389.6878
10866.36403.038510992.72414.084111027.13416.084211095.92395.836811160.85397.6507
#Mann= 3 , 0 , 0
 8846.85  0.0457       0 8846.85  0.0457       011160.85  0.0457       0
#XS Ineff= 2 , 0
       09913.984        10161.71       0
Bank Sta=8846.85,11160.85
Exp/Cntr=0.3,0.1

Type RM Length L Ch R = 1 ,9598.577,265.692500,265.692500,265.692500
XS GIS Cut Line= 6
636078.939387764751405.081764804635764.112694533752025.652255298
635672.954202507752229.841222479635608.044286893 752399.81072502
635542.841280319752537.411876911635004.282843813753542.407826573
#Sta/Elev= 30
8892.512497.62198966.984504.74759072.172479.3302 9218.22412.05749252.239392.1098
9274.393368.60699296.862353.2567  9341.8353.39219386.738366.69429431.676369.9244
9563.624365.05359653.802355.00469686.867344.1671 9849.62 338.58210087.82339.6285
10358.09364.805810420.46362.463910483.05350.854210562.68369.514510630.93378.1119
 10778.8378.5387 10869.8388.3824 10915.3380.762310983.46395.287511029.87385.5739
11062.78 391.85411119.45413.700911164.77416.4822 11210.1404.712211286.49414.6189
#Mann= 3 , 0 , 0
8892.512  0.0948       08892.512  0.0948       011286.49  0.0948       0
#XS Ineff= 2 , 0
       09870.787        10244.24       0
Bank Sta=8892.512,11286.49
Exp/Cntr=0.3,0.1

Type RM Length L Ch R = 1 ,9332.884,722.897400,722.897400,722.897400
XS GIS Cut Line= 6
635914.963534537750901.739474961635546.307060732751751.212687288
635458.036504515752033.453839344635306.878080497752635.861332662
635188.850446673752914.887106311634900.139653396753501.583695933
#Sta/Elev= 30
8556.329380.33158582.111381.36558670.699 363.7978692.692365.98328714.685361.7679
8747.674365.22778780.664 378.9488813.653380.79498857.639362.84438879.632358.5507
8956.607356.69429011.392361.49539086.198352.13019243.036353.32019964.618 338.582
10107.73341.991610189.96 338.58210283.29348.082710409.98347.092610474.51357.6289
10539.16358.954310648.59377.398510792.11380.946910896.28392.197210991.94393.1446
11058.94385.621411122.89389.291411181.96405.914211282.62418.285111357.08438.7535
#Mann= 3 , 0 , 0
8556.329   0.082       08556.329   0.082       011357.08   0.082       0
#XS Ineff= 2 , 0
       09704.481        10260.46       0
Bank Sta=8556.329,11357.08
Exp/Cntr=0.3,0.1

Type RM Length L Ch R = 1 ,8609.987,722.897500,722.897500,722.897500
XS GIS Cut Line= 6
635019.128982155751304.973422021634849.640984221751758.088172938
634782.360451187751920.710095305634656.920289369 752203.97081935
634591.380095644752367.297128815634451.485669712752772.718771179
#Sta/Elev= 30
9185.327408.37059217.336403.02669238.656 403.1419259.976407.25799291.956418.3923
9345.257423.33179398.558415.90459428.175404.33789441.198 396.7749485.907360.9288
9505.159349.33719515.819345.98729547.958347.87799580.097339.25439590.811 338.582
10112.31339.738510145.09344.987610199.11348.185510213.76347.741610240.61 338.626
10328.41340.829610360.31342.775810413.42356.399510527.74367.880710559.06373.4842
10590.66384.525310656.78400.3237 10688.4404.812410720.02403.931410759.79407.4874
#Mann= 3 , 0 , 0
9185.327  0.0414       09185.327  0.0414       010759.79  0.0414       0
#XS Ineff= 2 , 0
       0                               0
Bank Sta=9185.327,10759.79
Exp/Cntr=0.3,0.1

Type RM Length L Ch R = 1 ,7887.089,1844.948400,1844.948400,1844.948400
XS GIS Cut Line= 6
634043.812917533751265.425735237634025.924650282751577.701394826
634070.122988552751914.823745564634070.761099398752081.205732465
634053.441472739752310.415420726634018.016520619752549.315440521
#Sta/Elev= 30
9452.321424.66289472.012425.9494 9502.19421.2555 9522.31414.57219582.513390.7143
 9682.66365.6167 9692.66364.5645 9712.66365.36149732.661363.16059752.662357.0658
9762.662352.79149772.673346.21059792.702345.77429802.716347.55129812.731347.2697
 9832.76345.14549852.789340.82989882.944 338.58210485.97339.045610507.06351.1395
10547.41 369.32910577.68378.937410597.86382.856910628.13384.001910658.47389.9745
10688.89392.280410709.18392.156210719.32390.707410729.46385.893610743.98384.2892
#Mann= 3 , 0 , 0
9452.321  0.0232       09452.321  0.0232       010743.98  0.0232       0
#XS Ineff= 2 , 0
       0                               0
Bank Sta=9452.321,10743.98
Exp/Cntr=0.3,0.1

Type RM Length L Ch R = 1 ,6042.141,1446.245400,1446.245400,1446.245400
XS GIS Cut Line= 6
634076.571292231751023.209633444633010.502790712751200.094351657
632030.619023576 751677.24082613631630.556261016751786.498688975
631140.243030256751791.316659293629494.004610085751643.628331983
#Sta/Elev= 30
8264.739505.93388316.422  483.668376.551448.34248436.722424.73258466.832420.3638
8486.905409.62068587.366390.70438718.272379.49518758.618366.03158859.785349.2529
8920.707350.94639094.395339.38749156.187 343.6069187.257338.586211242.65 338.582
11402.89366.628711493.15  356.2411734.13344.513611774.63 338.58212055.87341.8728
12226.78367.981612337.32367.005912397.61360.925712467.95361.221812528.21368.4539
12558.31358.072312618.51371.7503 12708.8376.897912949.45406.668713000.54408.8888
#Mann= 3 , 0 , 0
8264.739  0.0146       08264.739  0.0146       013000.54  0.0146       0
#XS Ineff= 2 , 0
       0                11453.99       0
Bank Sta=8264.739,13000.54
Exp/Cntr=0.3,0.1

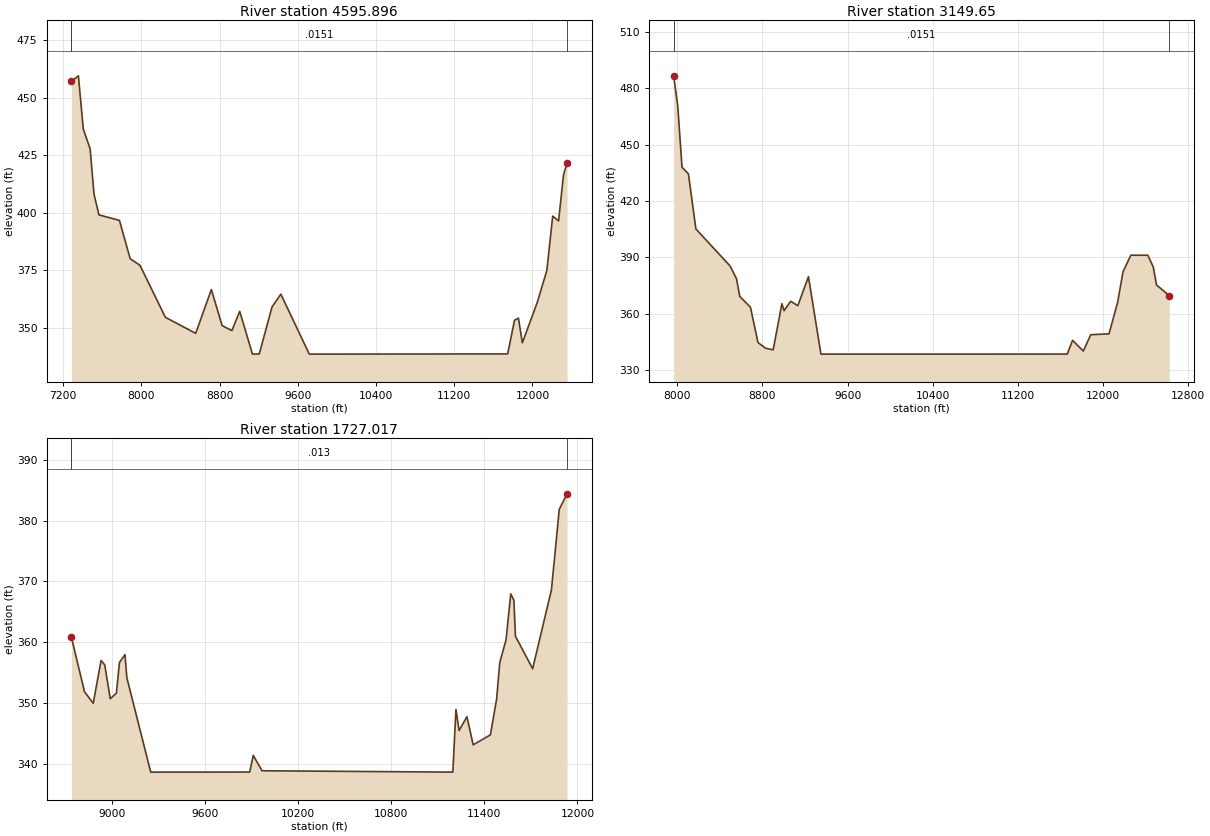
Type RM Length L Ch R = 1 ,4595.896,1446.245500,1446.245500,1446.245500
XS GIS Cut Line= 6
634236.129006542750260.462223353632533.293112949750292.965832554
631728.014329483750348.466353186631345.632077535750412.425910376
630893.576926876750456.609878509629178.348855034750550.617131727
#Sta/Elev= 30
7283.576457.03767354.705459.48787404.705436.39197474.705427.79467514.705408.0589
7564.705399.08537774.711396.66817884.716380.0198 7984.72377.17248244.744354.5672
8554.862347.6203 8714.95366.6379 8825.07 350.9638925.181348.80359005.281357.1636
9135.503 338.5829205.623338.68329335.911359.10539426.116364.63299716.946 338.582
11746.68338.673411816.76353.289811856.82354.237311896.89343.484812047.12360.7599
12147.27374.893112207.39 398.54212267.52396.452112317.64416.293912354.37421.8013
#Mann= 3 , 0 , 0
7283.576  0.0151       07283.576  0.0151       012354.37  0.0151       0
#XS Ineff= 2 , 0
       09411.581         11004.5       0
Bank Sta=7283.576,12354.37
Exp/Cntr=0.3,0.1

Type RM Length L Ch R = 1 , 3149.65,1422.632900,1422.632900,1422.632900
XS GIS Cut Line= 6
 634163.61796318749728.714572074632872.074683387749526.195489576
631875.368363404748936.965869661 631402.84163743748771.668655318
630700.145945681748731.483821935629737.807065284748872.242501009
#Sta/Elev= 30
7965.413486.53968004.093470.65468044.157 437.9478104.254434.45268174.418405.1411
8495.688385.44748556.096378.67568586.343369.29178687.298363.50128758.118344.7162
8829.245341.72138900.589340.86288982.497365.38629003.077361.68919064.934 366.689
9132.167364.32129231.982379.79129349.251 338.58211663.15338.609411713.29345.9371
11813.64340.227411884.05348.913712055.41349.357212136.24 366.05312186.89 382.293
12260.48391.186312420.37391.142912471.23384.921812501.83375.343512621.37369.6674
#Mann= 3 , 0 , 0
7965.413  0.0151       07965.413  0.0151       012621.37  0.0151       0
#XS Ineff= 2 , 0
       0 9196.76                       0
Bank Sta=7965.413,12621.37
Exp/Cntr=0.3,0.1

Type RM Length L Ch R = 1 ,1727.017,0.000000,0.000000,0.000000
XS GIS Cut Line= 6
633426.084046364748110.222261041632732.628445953747669.798455864
632222.054678202 747944.80707325631949.102424204748090.836529225
631304.796430707 748423.99570097630555.127539694748519.145482093
#Sta/Elev= 30
8740.931360.7954 8825.14351.82018881.239349.93458931.758356.97638955.451356.2454
 8990.99350.67619030.458351.59419050.222356.66729085.761 357.9519097.607 354.161
 9251.61 338.5829889.124338.59549911.841341.33959968.633338.807111197.21 338.582
11217.37348.915211237.53345.429111287.94347.719711328.26343.081811439.14344.7202
11479.46350.662111499.62356.666211539.94360.387311570.18367.952111590.34366.9121
11600.42  360.98 11711.3355.622311832.27368.625511882.67381.894711932.94384.4474
#Mann= 3 , 0 , 0
8740.931   0.013       08740.931   0.013       011932.94   0.013       0
#XS Ineff= 2 , 0
       09574.936                       0
Bank Sta=8740.931,11932.94
Exp/Cntr=0.3,0.1